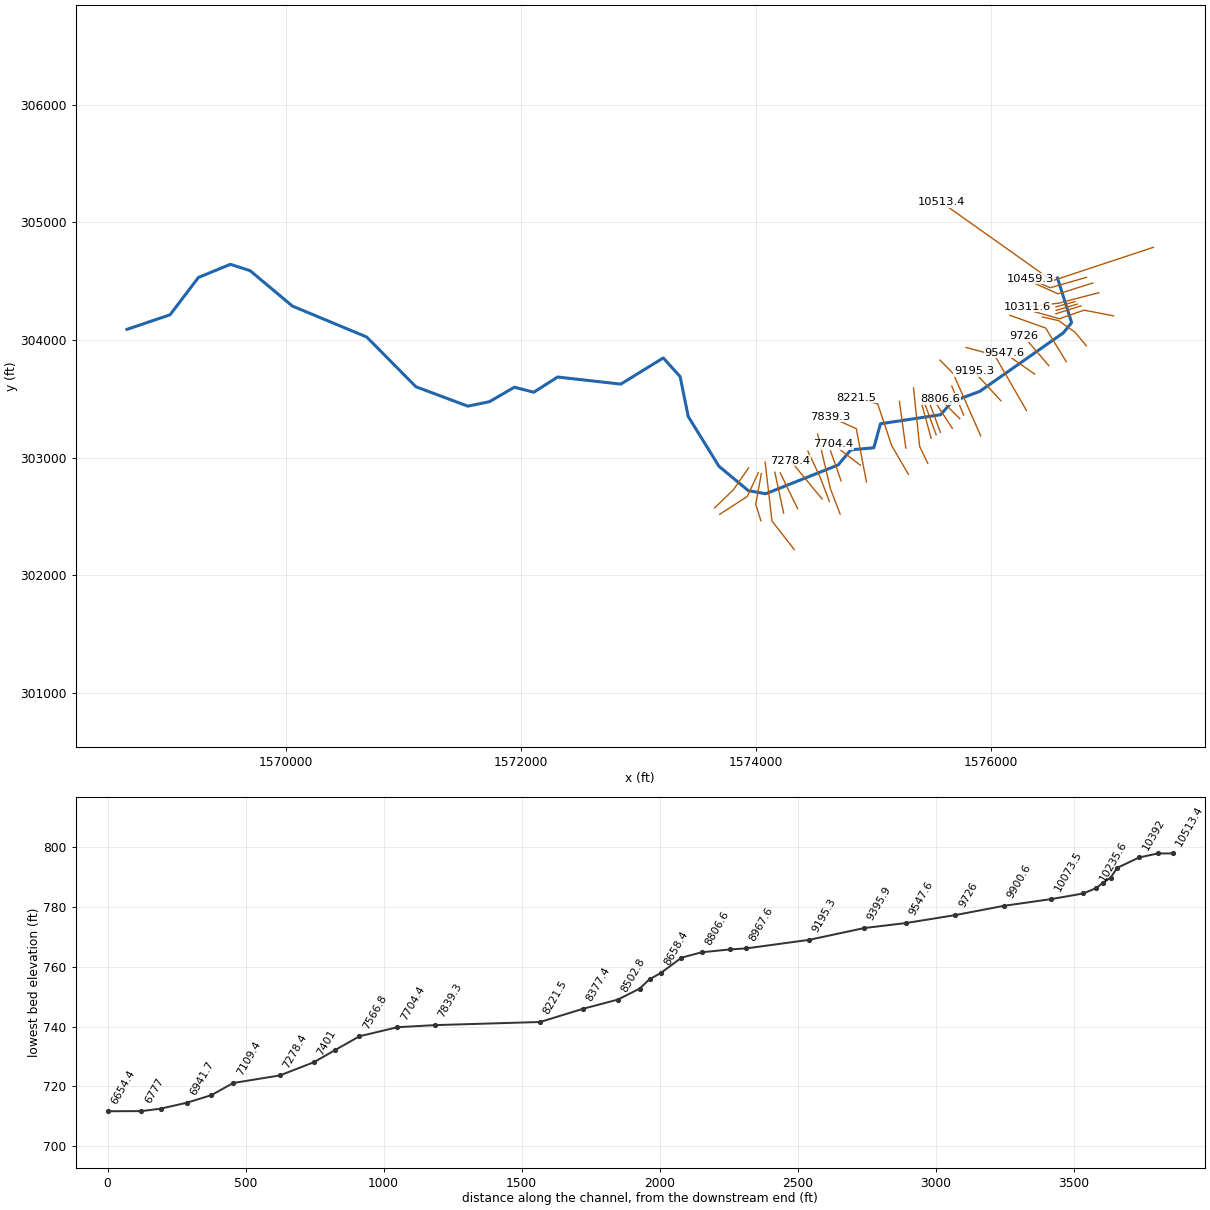
--- pprbrnngcr.prj (project) ---

Proj Title=pprbrnngcr
Current Plan=p01
Default Exp/Contr=0,0
English Units
Geom File=g01
Flow File=f01
Plan File=p01
BEGIN DESCRIPTION:
END DESCRIPTION:
DSS Export Rating Curves= 0
DSS Export Rating Curve Sorted= 0
DSS Export Volume Flow Curves= 0
DXF OffsetX= 0
DXF OffsetY= 0
DXF ScaleX= 0
DXF ScaleY= 0

--- pprbrnngcr.p01 (plan) ---

Plan Title=Floodplain
Program Version=4.00
Geom File=g01
Flow File=f01
K Sum by GR=0
Std Step Tol=0.01
Critical Tol=0.01
Num of Std Step Trials=20
Max Error Tol=0.3
Flow Tol Ratio=0.001
Split Flow NTrial=30
Split Flow Tol=0.02
Split Flow Ratio=0.02
Log Output Level=0
Friction Slope Method=1
Unsteady Friction Slope Method=2
Unsteady Bridges Friction Slope Method=1
Global Log Level=0
CheckData=False
Run HTab=0
Run UNet=0
Run PostProcess=0
UNET Theta=0
UNET Theta Warmup=0
UNET ZTol=0
UNET ZSATol=0
UNET MxIter=0
UNET MaxInSteps=0
UNET DtIC=0
UNET DtMin=0
UNET MaxCRTS=0
UNET WFStab=0
UNET SFStab=0
UNET WFX=0
UNET SFX=0
UNET DSS MLevel=0
UNET DZMax Abort=0
UNET Convert EG Bridges=0
UNET Use Existing IB Tables=0
UNET Froude Limit=0
UNET Froude Power=0
Write IC File=0
Echo Input=False
Echo Output=False
Write Detailed=0

--- pprbrnngcr.f01 (steady flow) ---

Flow Title=USGS Regression Equation
Program Version=4.00
Number of Profiles=1
Profile Names=P100yr
River Rch & RM=pprbrnngcr,Main      ,10513.4
     360
River Rch & RM=pprbrnngcr,Main      ,10188.8
     360
River Rch & RM=pprbrnngcr,Main      ,9900.6
     417
River Rch & RM=pprbrnngcr,Main      ,7477.7
     452
River Rch & RM=pprbrnngcr,Main      ,6598.8
     501
River Rch & RM=pprbrnngcr,Main      ,5419.3
     515
River Rch & RM=pprbrnngcr,Main      ,5077.6
     732
River Rch & RM=pprbrnngcr,Main      ,3287.9
     753
River Rch & RM=pprbrnngcr,Main      ,309.5
     832
Boundary for River Rch & Prof#=pprbrnngcr,Main      ,1
Up Type=0
Dn Type=3
Dn Slope=0.027385

--- pprbrnngcr.g01 (geometry) ---

Geom Title=USGS 3m DEM
Program Version=4.00

River Reach=pprbrnngcr      ,Main
Reach XY= 30
     1576565.867      304526.886     1576685.982      304147.067
     1576616.398      304061.031     1575905.075      303563.225
     1575669.119      303475.053     1575571.033      303364.346
     1575060.098      303287.787     1575002.907      303083.443
     1574807.789      303065.983     1574699.749      302937.356
      1574082.89      302692.719     1573935.533      302719.127
     1573685.803       302925.98     1573424.255      303348.939
     1573355.225      303688.412     1573211.767      303847.242
     1572850.241       303624.75       1572312.9      303684.895
     1572110.224      303555.847     1571944.809      303598.467
     1571733.601      303475.471     1571549.461      303437.481
     1571107.271      303601.976     1570688.832      304025.094
     1570056.465      304288.097     1569695.941      304589.248
     1569528.331      304643.088     1569256.414      304531.028
     1569015.576      304214.054     1568648.932        304090.2

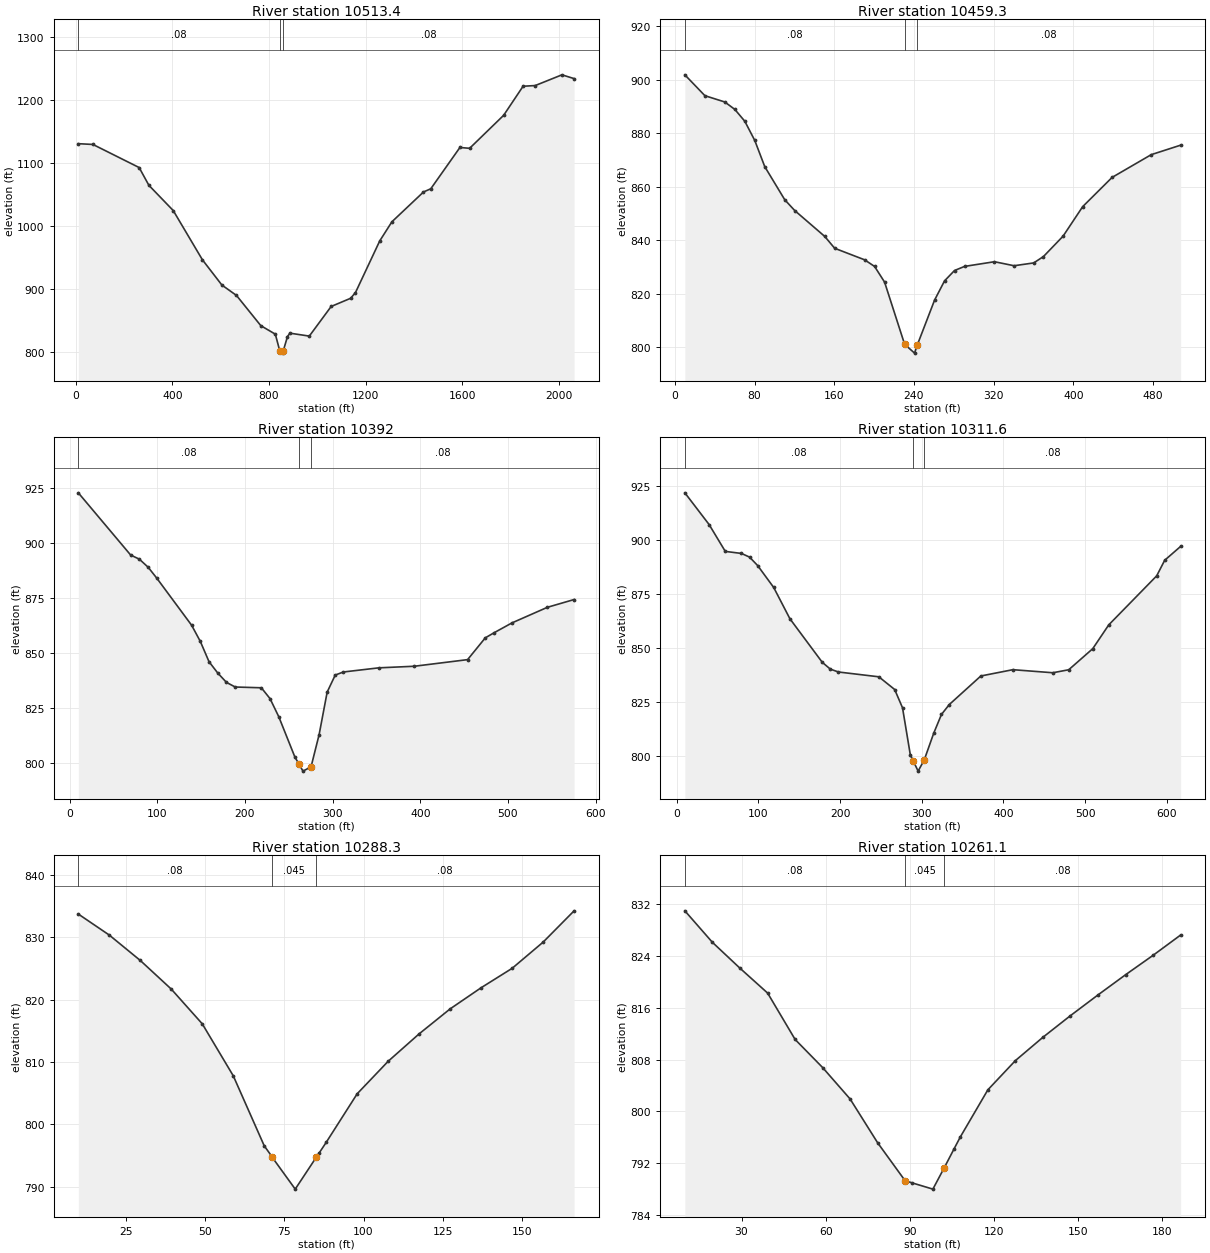
Type RM Length L Ch R = 1 ,10513.4 ,55,54,53.1
XS GIS Cut Line= 4
     1577381.964      304787.572     1576683.209      304556.535
     1576521.053      304502.881     1575576.637       305171.96
#Sta/Elev= 30
    10.1 1129.98    70.6 1128.77   262.1 1092.14   302.4 1063.97   403.3 1023.92
   524.2  945.79   604.9  905.74   665.4  889.23   766.1  841.33   826.4  827.77
   844.6   801.4   856.5  797.72  859.32   801.5   876.6  823.91   886.7  829.38
   967.1  824.74  1057.7  871.76  1138.2   884.7  1158.4   893.8    1259   975.8
  1309.3 1006.06  1440.2 1053.38  1470.4 1058.45  1591.1 1123.95  1631.4 1122.67
  1772.3    1175  1852.8 1221.12  1903.1 1222.21  2013.8 1239.23  2064.2 1233.25
#Mann= 3 , 0 , 0
    10.1     .08       0   844.6    .045       0  859.32     .08       0
Bank Sta=844.6,859.32
XS Rating Curve= 0 ,0
Exp/Cntr=0.3,0.1

Type RM Length L Ch R = 1 ,10459.3 ,67.3,67.4,67.4
XS GIS Cut Line= 3
     1576812.155      304532.291     1576503.746      304443.893
     1576332.844      304519.522
#Sta/Elev= 30
      10  901.83    30.1  894.03    50.1  891.67    60.2  888.88    70.2  884.45
    80.2  877.26    90.2  867.48   110.3  855.08   120.3  851.05   150.4  841.38
   160.4  836.93   190.5  832.61   200.5  830.12   210.5  824.27   230.6  801.02
   240.6   797.7  243.53  800.92   260.7  817.55   270.7  824.74   280.7  828.61
   290.8  830.15   320.8   831.9   340.5   830.4   360.2  831.45     370  833.84
   389.7  841.47   409.4  852.52   438.9  863.45   478.2  871.96   507.7  875.51
#Mann= 3 , 0 , 0
      10     .08       0   230.6    .045       0  243.53     .08       0
Bank Sta=230.6,243.53
XS Rating Curve= 0 ,0
Exp/Cntr=0.3,0.1

Type RM Length L Ch R = 1 ,10392   ,80.8,80.3,79.9
XS GIS Cut Line= 4
      1576867.01      304484.677      1576639.48      304412.934
     1576568.761      304392.435     1576328.932      304501.076
#Sta/Elev= 30
     9.9   922.8    69.6  894.54    79.5  892.67    89.5  889.02    99.4  884.04
   139.2  862.62   149.1  855.28     159  846.09     169  840.92   178.9  836.69
   188.9  834.59   218.7  834.24   228.6  829.32   238.6  821.08     257  802.74
  261.53  799.66   266.2  796.38   275.4  798.33   284.6  812.95   293.8   832.3
     303  840.02   312.2  841.41   352.7   843.3   393.2  844.02     454  847.03
   474.2  856.93   484.4  859.28   504.6  863.71   545.1  870.81   575.5  874.33
#Mann= 3 , 0 , 0
     9.9     .08       0  261.53    .045       0   275.4     .08       0
Bank Sta=261.53,275.4
XS Rating Curve= 0 ,0
Exp/Cntr=0.3,0.1

Type RM Length L Ch R = 1 ,10311.6 ,23,23.3,23.5
XS GIS Cut Line= 4
     1576917.231      304401.659     1576668.177       304337.09
     1576575.935      304312.492     1576313.558      304281.745
#Sta/Elev= 30
     9.9     922    39.6  907.28    59.4  894.83    79.2  893.88    89.1  892.18
      99  888.27   118.7  878.08   138.5  863.59   178.1  843.39     188  840.21
   197.9  838.88   247.4  836.65   266.8  830.75   276.4  822.26   285.9  800.55
  289.38  797.72   295.5  792.89     303   798.1   314.6  810.48   324.1   819.2
   333.7   823.8   372.3  837.03   411.5  839.95   460.4  838.53   479.9  839.92
   509.3  849.69   528.9  860.74   587.6  883.49   597.4  890.72   616.9  897.14
#Mann= 3 , 0 , 0
     9.9     .08       0  289.38    .045       0     303     .08       0
Bank Sta=289.38,303
XS Rating Curve= 0 ,0
Exp/Cntr=0.3,0.1

Type RM Length L Ch R = 1 ,10288.3 ,26.9,27.3,27.6
XS GIS Cut Line= 2
     1576713.709      304325.994     1576553.181      304281.318
#Sta/Elev= 21
     9.8  833.73    19.6  830.36    29.4  826.29    39.2   821.7      49  816.13
    58.8   807.8    68.6  796.57    70.9  794.94    71.1  794.75    78.4  789.63
   85.07  794.75    85.9  795.37    88.2  797.13      98  804.92   107.8  810.13
   117.6  814.53   127.4  818.53   137.2  821.92     147  825.03   156.8  829.23
   166.6  834.25
#Mann= 3 , 0 , 0
     9.8     .08       0    71.1    .045       0   85.07     .08       0
Bank Sta=71.1,85.07
XS Rating Curve= 0 ,0
Exp/Cntr=0.3,0.1

Type RM Length L Ch R = 1 ,10261.1 ,25.2,25.5,25.9
XS GIS Cut Line= 2
     1576733.644      304304.894     1576554.876      304251.746
#Sta/Elev= 22
     9.8  830.99    19.6  826.13    29.4  822.14    39.3  818.28    49.1  811.11
    58.9  806.77    68.7  801.91    78.5  795.15    88.3  789.28    90.7  788.96
    98.2  787.98  102.23  791.27   105.7  794.16     108  796.06   117.8  803.33
   127.6  807.84   137.4  811.44   147.2  814.78   157.1  818.01   166.9  821.12
   176.7  824.12   186.5  827.25
#Mann= 3 , 0 , 0
     9.8     .08       0    88.3    .045       0  102.23     .08       0
Bank Sta=88.3,102.23
XS Rating Curve= 0 ,0
Exp/Cntr=0.3,0.1

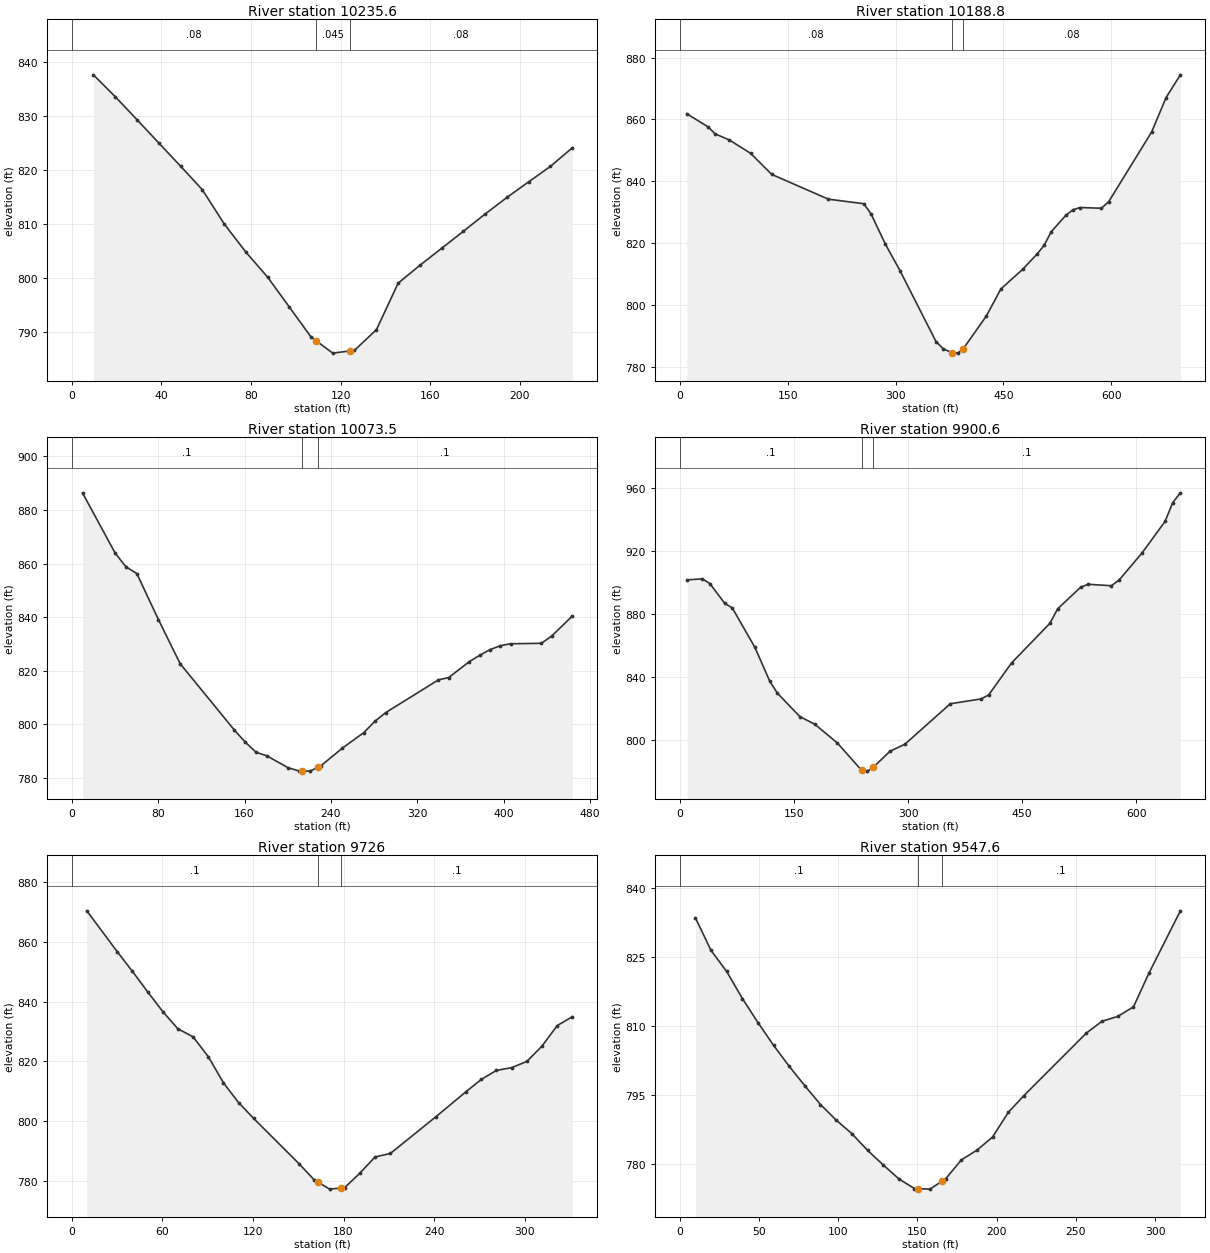
Type RM Length L Ch R = 1 ,10235.6 ,46,46.7,47.5
XS GIS Cut Line= 2
     1576765.992      304289.689     1576552.856        304222.9
#Sta/Elev= 25
     9.7  837.61    19.4  833.58    29.1  829.33    38.8  825.03    48.6  820.71
    58.3  816.36      68  810.07    77.7  804.83    87.4  800.21    97.1  794.67
   106.8  789.12     109  788.44   116.5  786.13     124  786.53   126.2  786.65
     136  790.48   145.7  799.08   155.4  802.38   165.1  805.52   174.8  808.67
   184.5  811.86   194.2  814.92   203.9  817.81   213.6  820.66   223.4  824.11
#Mann= 3 , 0 , 0
       0     .08       0     109    .045       0     124     .08       0
Bank Sta=109,124
XS Rating Curve= 0 ,0
Exp/Cntr=0.3,0.1

Type RM Length L Ch R = 1 ,10188.8 ,137.8,115.4,92.9
XS GIS Cut Line= 4
     1577042.971       304205.22     1576791.652      304253.225
     1576583.181      304180.297     1576371.978      304239.723
#Sta/Elev= 30
     9.8  861.86    39.4   857.6    49.2  855.35    68.9  853.37    98.4  849.06
   127.9  842.22   206.7   834.2   255.9  832.73   265.9  829.46     286   819.6
   306.1  811.11   356.3   788.1   366.3  785.78   378.9  784.44   386.4  784.36
   393.9  785.67   426.5  796.45   446.6  805.17   476.7  811.47   496.7  816.42
   506.6  819.24   516.6  823.69   536.6  828.92   546.5  830.75   556.5   831.5
   586.4  831.27   596.4  833.38   656.2  855.98   676.2   867.1   696.1  874.46
#Mann= 3 , 0 , 0
       0     .08       0   378.9    .045       0   393.9     .08       0
Bank Sta=378.9,393.9
XS Rating Curve= 0 ,0
Exp/Cntr=0.3,0.1

Type RM Length L Ch R = 1 ,10073.5 ,182,172.8,163.7
XS GIS Cut Line= 4
     1576811.665      303949.674     1576715.323      304065.489
      1576576.96       304163.88     1576437.572      304195.652
#Sta/Elev= 30
      10   886.4    40.2  863.91    50.2  858.79    60.3  856.26    80.3  839.05
   100.4   822.6   150.6  797.81   160.6  793.35   170.6  789.55   180.6   788.2
   200.6  783.71   210.6  782.55   213.1  782.53   220.6  782.49   228.1  783.95
   230.5  784.41   250.5  791.06   270.5  796.91   280.5  801.04   290.5   804.3
   339.5  816.57     349  817.43   368.1  823.38   377.6  825.72   387.1  827.83
   396.7  829.31   406.2  830.04   434.8  830.22   444.3  832.92   463.4  840.39
#Mann= 3 , 0 , 0
       0      .1       0   213.1    .045       0   228.1      .1       0
Bank Sta=213.1,228.1
XS Rating Curve= 0 ,0
Exp/Cntr=0.3,0.1

Type RM Length L Ch R = 1 ,9900.6  ,171.1,174.6,178.2
XS GIS Cut Line= 3
     1576640.505       303815.41     1576465.245      304101.361
     1576161.227      304209.381
#Sta/Elev= 30
     9.9  901.45    29.6   902.1    39.5  899.15    59.2  886.52      69  883.69
    98.6  858.82   118.4  837.11   128.2  829.71   157.8   814.8   177.6  809.92
   207.1  798.08   239.1  780.72   246.6  780.23   254.1  782.55   276.2  792.79
   295.9  797.29   355.6  822.93   395.9  825.98     406   828.5   436.2  848.86
   486.6  873.97   496.7  883.12     527  896.83     537  898.66   567.3  897.74
   577.4  901.31   607.6  918.52   637.9  938.52   647.9   950.4     658  956.63
#Mann= 3 , 0 , 0
       0      .1       0   239.1    .045       0   254.1      .1       0
Bank Sta=239.1,254.1
XS Rating Curve= 0 ,0
Exp/Cntr=0.3,0.1

Type RM Length L Ch R = 1 ,9726    ,172.6,178.4,184.2
XS GIS Cut Line= 2
     1576491.893      303781.588     1576276.661      304033.716
#Sta/Elev= 29
      10  870.42    30.1  856.78    40.2  850.14    50.2  843.35    60.3  836.67
    70.3   830.9    80.4  828.18    90.4  821.59   100.5  812.78   110.5  806.16
   120.5  800.85   150.7  785.59   160.7  780.21   163.3  779.43   170.8  777.16
   178.3  777.55   180.8  777.68   190.9  782.54   200.9  787.95     211   789.1
   241.1  801.39   261.2  809.84   271.2  813.91   281.3  816.95   291.3  817.87
   301.4  819.95   311.4  825.08   321.5  831.95   331.5  834.94
#Mann= 3 , 0 , 0
       0      .1       0   163.3    .045       0   178.3      .1       0
Bank Sta=163.3,178.3
XS Rating Curve= 0 ,0
Exp/Cntr=0.3,0.1

Type RM Length L Ch R = 1 ,9547.6  ,161.6,151.6,141.7
XS GIS Cut Line= 2
     1576371.978      303709.844     1576112.675      303890.229
#Sta/Elev= 30
     9.9  833.49    19.7  826.42    29.6  821.83    39.5  815.95    49.4   810.7
    59.2  805.77    69.1   801.2      79  796.95    88.8  792.91    98.7  789.52
   108.6  786.57   118.5  782.95   128.3   779.8   138.2  776.75   148.1  774.64
   150.4  774.61   157.9  774.51   165.4  776.22   167.8  776.77   177.7  780.87
   187.6     783   197.4  785.85   207.3   791.2   217.2  794.86   256.6  808.45
   266.5  811.02   276.4  812.06   286.3  814.14   296.1   821.5   315.9  835.02
#Mann= 3 , 0 , 0
       0      .1       0   150.4    .045       0   165.4      .1       0
Bank Sta=150.4,165.4
XS Rating Curve= 0 ,0
Exp/Cntr=0.3,0.1

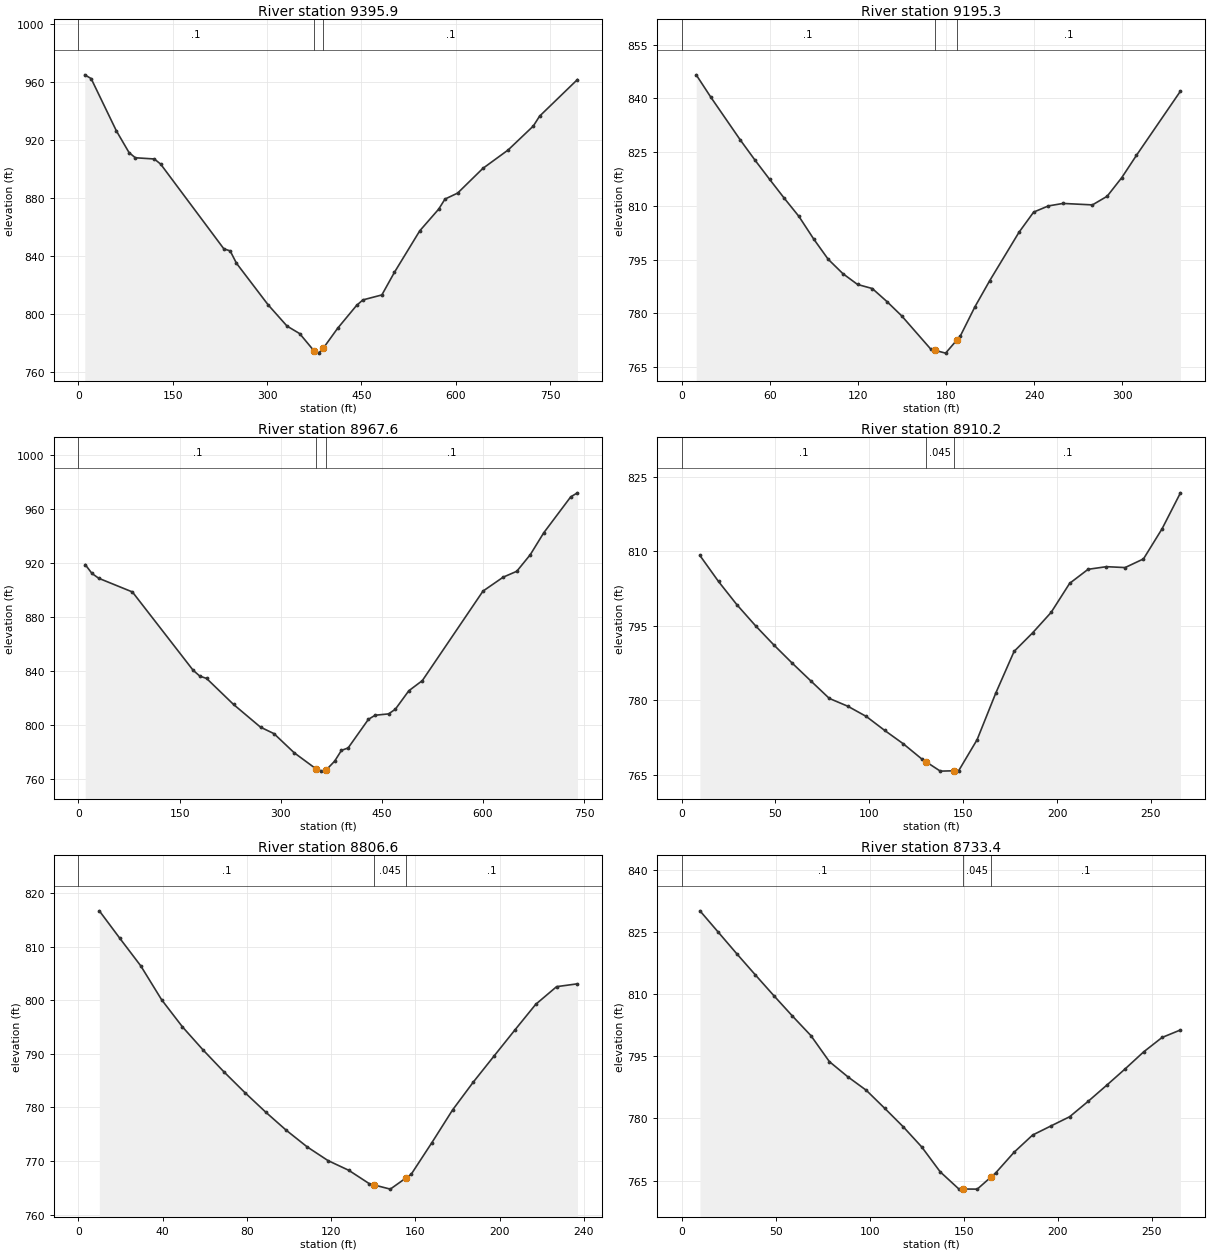
Type RM Length L Ch R = 1 ,9395.9  ,195.2,200.7,206.2
XS GIS Cut Line= 3
     1576301.888      303400.697     1576030.683      303870.755
     1575788.699      303936.324
#Sta/Elev= 30
      10  964.85    20.1  962.27    60.3  926.15    80.4   911.2    90.4  907.63
   120.6  906.79   130.6  903.28   231.1  844.82   241.2  843.36   251.2  834.87
   301.5  806.19   331.6  791.51   351.7  786.31   374.4  774.48   381.9  772.84
   389.4  776.33     412  789.94   442.2  805.76   452.2  809.55   482.4  812.99
   502.5  828.68   542.7  857.25   572.8  872.21   582.8  879.14   602.9  883.25
     643  900.29   683.1  912.97   723.2  929.51   733.2  936.33   793.4  961.59
#Mann= 3 , 0 , 0
       0      .1       0   374.4    .045       0   389.4      .1       0
Bank Sta=374.4,389.4
XS Rating Curve= 0 ,0
Exp/Cntr=0.3,0.1

Type RM Length L Ch R = 1 ,9195.3  ,235.2,227.7,220.2
XS GIS Cut Line= 2
     1576083.978      303483.339     1575854.398      303733.417
#Sta/Elev= 30
      10   846.6      20  840.32    39.9  828.47    49.9  822.83    59.9  817.44
    69.9  812.15    79.9  807.06    89.9  800.78    99.8   795.1   109.8  791.08
   119.8  788.06   129.8  786.93   139.8  783.28   149.8   779.3   169.7  769.96
   172.2  769.69   179.7  768.89   187.2  772.47   189.7  773.67   199.7  781.87
   209.7  789.12   229.6  802.62   239.6  808.27   249.6  809.99   259.6  810.69
   279.6  810.28   289.6  812.69   299.5  817.86   309.5  824.09   339.5  842.05
#Mann= 3 , 0 , 0
       0      .1       0   172.2    .045       0   187.2      .1       0
Bank Sta=172.2,187.2
XS Rating Curve= 0 ,0
Exp/Cntr=0.3,0.1

Type RM Length L Ch R = 1 ,8967.6  ,58.1,57.4,56.8
XS GIS Cut Line= 3
     1575913.076       303184.17     1575678.425      303714.572
     1575566.082      303828.698
#Sta/Elev= 30
      10  918.78      20  912.24      30  908.67      80  898.54     170  840.66
     180   836.3     190  834.59     230  815.35     270  798.56     290  793.76
     320   779.6   352.5  767.67     360  766.04   367.5  766.96     380  773.44
     390  781.36     400   783.2     430  804.32     440  807.37     460  808.37
     470  811.83     490  825.49     510  832.97     600  899.18     630   909.5
   650.1  913.83   670.1  926.08   690.1  942.28   730.1  968.86   740.1  971.86
#Mann= 3 , 0 , 0
       0      .1       0   352.5    .045       0   367.5      .1       0
Bank Sta=352.5,367.5
XS Rating Curve= 0 ,0
Exp/Cntr=0.3,0.1

Type RM Length L Ch R = 1 ,8910.2  ,94.7,103.6,112.5
XS GIS Cut Line= 2
      1575767.28      303361.375     1575666.839      303607.354
#Sta/Elev= 29
     9.8  809.11    19.7  803.88    29.5   799.2    39.4  794.98    49.2   791.1
      59  787.43    68.9  783.86    78.7  780.35    88.6  778.77    98.4  776.72
   108.2  773.91   118.1  771.22   127.9  768.18   130.3  767.58   137.8  765.72
   145.3  765.79   147.6  765.81   157.4  772.04   167.3  781.38   177.1  789.81
     187  793.56   196.8  797.65   206.7  803.51   216.5  806.33   226.3  806.86
   236.2  806.68     246  808.42   255.9  814.48   265.7  821.72
#Mann= 3 , 0 , 0
       0      .1       0   130.3    .045       0   145.3      .1       0
Bank Sta=130.3,145.3
XS Rating Curve= 0 ,0
Exp/Cntr=0.3,0.1

Type RM Length L Ch R = 1 ,8806.6  ,77.9,73.2,68.5
XS GIS Cut Line= 2
     1575734.483      303330.627     1575567.423      303498.713
#Sta/Elev= 26
     9.9  816.68    19.7  811.52    29.6   806.4    39.5  800.08    49.4  795.02
    59.2  790.71    69.1  786.63      79  782.78    88.9  779.13    98.7  775.73
   108.6  772.64   118.5  770.08   128.4  768.26   138.2  765.75   140.6  765.51
   148.1  764.75   155.6  766.84     158   767.5   167.9  773.45   177.7  779.53
   187.6  784.76   197.5  789.64   207.4   794.5   217.2  799.24   227.1  802.53
     237  803.06
#Mann= 3 , 0 , 0
       0      .1       0   140.6    .045       0   155.6      .1       0
Bank Sta=140.6,155.6
XS Rating Curve= 0 ,0
Exp/Cntr=0.3,0.1

Type RM Length L Ch R = 1 ,8733.4  ,80.2,75,69.8
XS GIS Cut Line= 2
     1575670.939      303248.635     1575526.426       303471.04
#Sta/Elev= 29
     9.8  830.07    19.6  824.89    29.5  819.65    39.3  814.59    49.1   809.6
    58.9  804.72    68.8  799.96    78.6   793.7    88.4  790.04    98.2  786.79
   108.1   782.4   117.9  777.96   127.7  773.11   137.5  767.12   147.4  762.99
   149.7  762.98   157.2  762.95   164.7  765.95     167  766.87   176.8  771.86
   186.6  775.99   196.5  778.22   206.3  780.41   216.1  784.11   225.9  787.97
   235.8  791.95   245.6  796.04   255.4  799.52   265.2  801.34
#Mann= 3 , 0 , 0
       0      .1       0   149.7    .045       0   164.7      .1       0
Bank Sta=149.7,164.7
XS Rating Curve= 0 ,0
Exp/Cntr=0.3,0.1

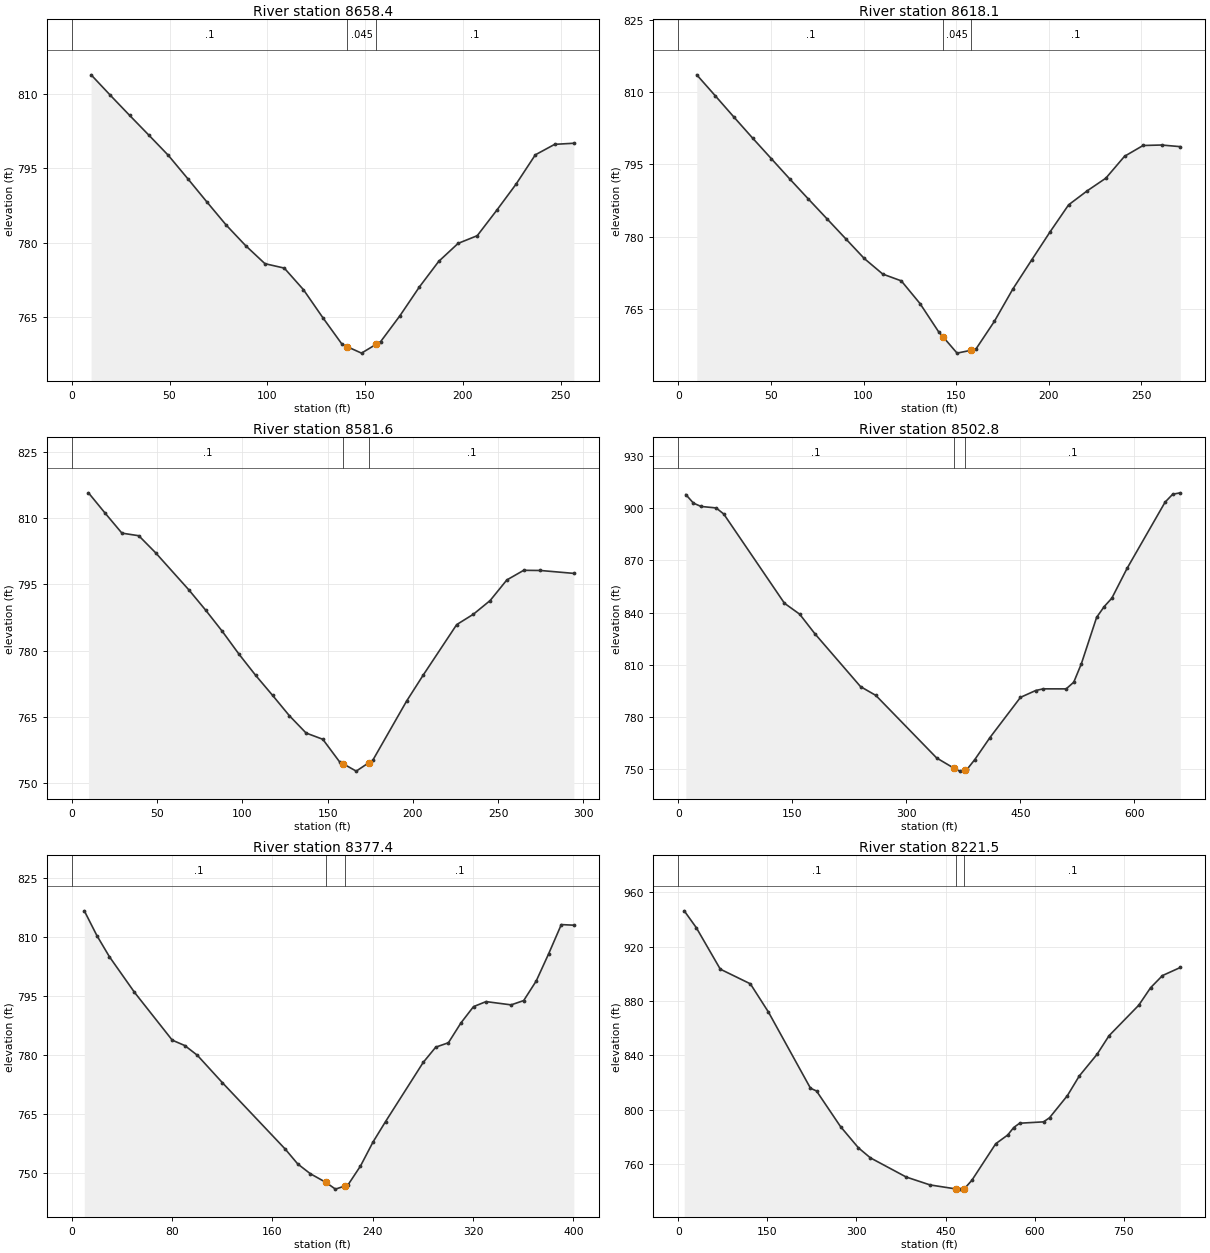
Type RM Length L Ch R = 1 ,8658.4  ,40.4,40.3,40.2
XS GIS Cut Line= 2
     1575569.472      303214.813     1575480.305      303455.667
#Sta/Elev= 28
     9.9   813.8    19.8  809.66    29.6  805.64    39.5  801.64    49.4   797.6
    59.3  792.93    69.1  788.24      79  783.58    88.9  779.46    98.8  775.82
   108.7  774.93   118.5  770.59   128.4  764.97   138.3  759.58   140.7  759.16
   148.2  757.83   155.7  759.61     158  760.15   167.9  765.38   177.8  771.14
   187.7  776.29   197.6   779.9   207.4  781.45   217.3  786.53   227.2  791.79
   237.1  797.71     247  799.82   256.8  800.04
#Mann= 3 , 0 , 0
       0      .1       0   140.7    .045       0   155.7      .1       0
Bank Sta=140.7,155.7
XS Rating Curve= 0 ,0
Exp/Cntr=0.3,0.1

Type RM Length L Ch R = 1 ,8618.1  ,38.4,36.5,34.6
XS GIS Cut Line= 2
     1575533.391      303194.733     1575440.159      303449.153
#Sta/Elev= 29
      10   813.6    20.1   809.2    30.1  804.81    40.1  800.48    50.2   796.2
    60.2  791.97    70.2  787.82    80.3  783.69    90.3  779.59   100.4  775.45
   110.4  772.21   120.4   770.8   130.5  766.09   140.5  760.25     143  759.14
   150.5  755.79     158  756.38   160.6  756.59   170.6  762.37   180.6   769.1
   190.7   775.1   200.7  780.98   210.7  786.59   220.8  789.52   230.8  792.13
   240.9  796.68   250.9  798.92   260.9  799.02     271  798.68
#Mann= 3 , 0 , 0
       0      .1       0     143    .045       0     158      .1       0
Bank Sta=143,158
XS Rating Curve= 0 ,0
Exp/Cntr=0.3,0.1

Type RM Length L Ch R = 1 ,8581.6  ,82.4,78.8,75.1
XS GIS Cut Line= 2
     1575490.555      303165.617     1575412.661      303449.517
#Sta/Elev= 28
     9.8  815.81    19.6  811.18    29.4  806.66    39.3  806.07    49.1  802.23
    68.7  793.76    78.5  789.18    88.3  784.35    98.1  779.16   107.9  774.34
   117.8  769.81   127.6  765.21   137.4  761.28   147.2  759.86     157  754.76
   159.3  754.26   166.8  752.63   174.3  754.57   176.6  755.16   196.3  768.51
   206.1  774.45   225.7  785.89   235.5  788.25   245.3  791.35   255.1  796.03
     265  798.22   274.8  798.18   294.4  797.52
#Mann= 3 , 0 , 0
       0      .1       0   159.3    .045       0   174.3      .1       0
Bank Sta=159.3,174.3
XS Rating Curve= 0 ,0
Exp/Cntr=0.3,0.1

Type RM Length L Ch R = 1 ,8502.8  ,124.7,125.4,126.1
XS GIS Cut Line= 3
     1575462.627      302950.967     1575393.188      303094.898
     1575340.917      303593.005
#Sta/Elev= 30
      10  907.79      20  902.87      30  900.96    49.9   900.1    59.9  896.61
   139.8  845.35   159.8  839.09   179.8  827.86   239.9  797.49     260  792.45
   340.1   756.5   362.7  750.67   370.2  748.97   377.7  749.83   380.2  750.12
   390.2  755.61   410.2  768.28   450.3  791.33   470.3  795.26   480.3  796.22
   510.4   796.2   520.4  800.04   530.4  810.62   550.5  837.28   560.5  843.48
   570.5  848.28   590.5  865.36   640.6  903.45   650.6  907.98   660.6  908.78
#Mann= 3 , 0 , 0
       0      .1       0   362.7    .045       0   377.7      .1       0
Bank Sta=362.7,377.7
XS Rating Curve= 0 ,0
Exp/Cntr=0.3,0.1

Type RM Length L Ch R = 1 ,8377.4  ,151.7,155.9,160.2
XS GIS Cut Line= 2
     1575275.323      303081.574     1575221.003      303478.215
#Sta/Elev= 30
      10  816.69      20  810.41      30  805.03      50  795.97    80.1  783.81
    90.1  782.44   100.1  779.97   120.1  772.99   170.1  756.14   180.2  752.32
   190.2  749.85   202.7  747.63   210.2  745.93   217.7  746.72   220.2  746.99
   230.2  751.81   240.2  757.92   250.2  763.12   280.2  778.15   290.2  782.03
   300.3  783.15   310.3   788.2   320.3  792.33   330.3  793.61   350.3  792.78
   360.3  793.87   370.3  798.85   380.3  805.83   390.3  813.19   400.3  813.04
#Mann= 3 , 0 , 0
       0      .1       0   202.7    .045       0   217.7      .1       0
Bank Sta=202.7,217.7
XS Rating Curve= 0 ,0
Exp/Cntr=0.3,0.1

Type RM Length L Ch R = 1 ,8221.5  ,385.1,382.2,379.3
XS GIS Cut Line= 4
     1575296.602      302859.044     1575154.384      303104.122
     1575036.519      303456.691     1574853.524      303508.347
#Sta/Elev= 30
    10.1  946.27    30.4  933.88    70.8  903.35   121.4  892.57   151.8  871.83
   222.6  815.77   232.8  813.71   273.2  787.52   303.4  771.86   323.5  764.52
   383.8  750.41     424  744.59   466.8   741.7   474.3  741.51   481.8  741.88
   494.3  748.02   534.5  774.92   554.6  781.31   564.7  786.82   574.7     790
   614.9     791     625     794   655.1   810.3   675.1  824.74   705.1  840.74
   725.2  854.38   775.2  876.81   795.2  889.72   815.2  898.65   845.2  904.58
#Mann= 3 , 0 , 0
       0      .1       0   466.8    .045       0   481.8      .1       0
Bank Sta=466.8,481.8
XS Rating Curve= 0 ,0
Exp/Cntr=0.3,0.1

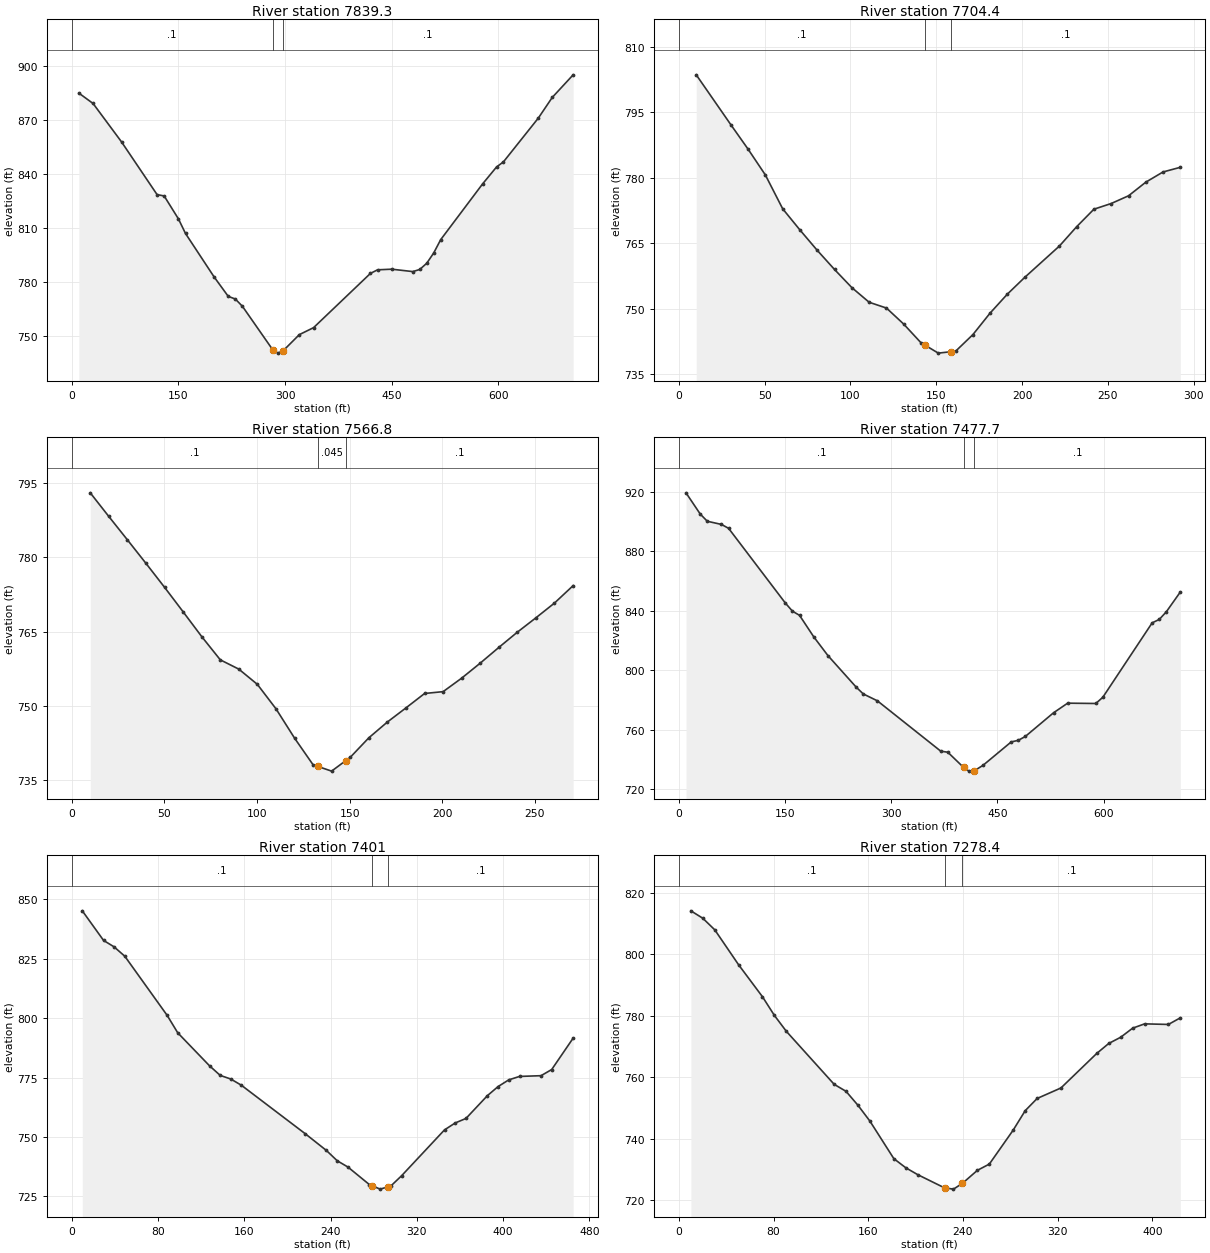
Type RM Length L Ch R = 1 ,7839.3  ,118.5,135,151.5
XS GIS Cut Line= 3
     1574940.177      302793.574     1574854.085       303245.56
     1574630.964      303347.042
#Sta/Elev= 30
      10  884.76      30     879      70   857.7     120  828.44     130  827.67
     150     815     160  806.86     200  782.88   220.1  771.96   230.1  770.48
   240.1  766.42   282.6  742.36   290.1  740.46   297.6  741.88   320.1  750.73
   340.1  754.59   420.1  784.71   430.1  786.69   450.1  787.04   479.7  785.71
   489.5  786.89   499.3  790.35   509.1  796.05   518.9  803.43   577.8  834.35
   597.4  843.74   607.2  846.62   656.2  870.89   675.8  882.36   705.2   894.9
#Mann= 3 , 0 , 0
       0      .1       0   282.6    .045       0   297.6      .1       0
Bank Sta=282.6,297.6
XS Rating Curve= 0 ,0
Exp/Cntr=0.3,0.1

Type RM Length L Ch R = 1 ,7704.4  ,150.6,137.5,124.5
XS GIS Cut Line= 2
     1574888.932      302935.012     1574657.302      303113.346
#Sta/Elev= 29
    10.1  803.57    30.2  792.17    40.3  786.54    50.4  780.61    60.5  772.85
    70.6  767.98    80.6  763.35    90.7  758.95   100.8  754.79   110.9  751.43
     121   750.1     131  746.44   141.1  742.15   143.7  741.54   151.2  739.77
   158.7   740.1   161.3  740.21   171.4  744.03   181.4  748.95   191.5  753.31
   201.6  757.14   221.8  764.32   231.8  768.73   241.9  772.76     252  774.07
   262.1  775.84   272.2  778.97   282.2   781.3   292.3  782.37
#Mann= 3 , 0 , 0
       0      .1       0   143.7    .045       0   158.7      .1       0
Bank Sta=143.7,158.7
XS Rating Curve= 0 ,0
Exp/Cntr=0.3,0.1

Type RM Length L Ch R = 1 ,7566.8  ,91.6,89.1,86.6
XS GIS Cut Line= 2
     1574724.946      302801.773     1574634.754      303056.976
#Sta/Elev= 29
      10  793.09      20  788.31    30.1  783.55    40.1   778.8    50.1  773.97
    60.1  769.02    70.2  763.97    80.2  759.28    90.2   757.4   100.2  754.32
   110.3  749.35   120.3  743.43   130.3  738.03   132.8  737.71   140.3  736.75
   147.8  738.84   150.4  739.56   160.4   743.5   170.4  746.69   180.4  749.54
   190.5  752.47   200.5  752.84   210.5  755.57   220.5   758.6   230.6   761.8
   240.6  764.89   250.6  767.79   260.6  770.77   270.7  774.31
#Mann= 3 , 0 , 0
       0      .1       0   132.8    .045       0   147.8      .1       0
Bank Sta=132.8,147.8
XS Rating Curve= 0 ,0
Exp/Cntr=0.3,0.1

Type RM Length L Ch R = 1 ,7477.7  ,72,76.8,81.6
XS GIS Cut Line= 3
     1574716.721      302520.099     1574633.729      302735.154
     1574525.088      303200.464
#Sta/Elev= 30
      10  919.21    30.1  904.95    40.1  900.09    60.1  897.97    70.2  895.33
   150.3  845.13   160.4  839.63   170.4  836.83   190.4  822.42   210.5  809.77
   250.4  788.57   260.4     784   280.3  779.38   369.9  745.51   379.8  744.82
   402.2  734.55   409.7   732.1   417.2  732.32   429.6  736.01   469.4  751.74
   479.4  752.81   489.3   755.4   529.2  771.34   549.1  777.79   588.9  777.57
   598.8  781.76   668.5   831.8   678.5  834.09   688.4  839.16   708.3  852.55
#Mann= 3 , 0 , 0
       0      .1       0   402.2    .045       0   417.2      .1       0
Bank Sta=402.2,417.2
XS Rating Curve= 0 ,0
Exp/Cntr=0.3,0.1

Type RM Length L Ch R = 1 ,7401    ,117,122.6,128.2
XS GIS Cut Line= 3
     1574624.823       302627.37     1574548.211      302829.702
     1574442.134      303054.625
#Sta/Elev= 30
     9.8  845.12    29.5  832.68    39.3  829.96    49.2  826.03    88.5  801.14
    98.3  793.82   127.8  779.93   137.7   775.9   147.5  774.38   157.3  771.77
   216.4  751.42   236.2  744.32   246.2     740   256.1  737.37     276  729.99
   278.5  729.51     286  728.07   293.5  729.06   295.9  729.37   305.9   733.7
   345.7  752.99   355.6  755.89   365.6   757.8   385.5   767.4   395.4  771.21
   405.3  774.03   415.3  775.47   435.2  775.78   445.1  778.37     465  791.58
#Mann= 3 , 0 , 0
       0      .1       0   278.5    .045       0   293.5      .1       0
Bank Sta=278.5,293.5
XS Rating Curve= 0 ,0
Exp/Cntr=0.3,0.1

Type RM Length L Ch R = 1 ,7278.4  ,174.3,168.9,163.6
XS GIS Cut Line= 2
      1574563.01      302648.037     1574293.458      302974.983
#Sta/Elev= 30
    10.1  814.15    20.2  811.73    30.3  807.97    50.4  796.63    70.6  786.22
    80.7  780.14    90.8  774.97   131.2  757.75   141.2  755.48   151.3  750.94
   161.4  745.79   181.6   733.6   191.7  730.63   201.8  728.39   224.5  724.09
     232  723.69   239.5  725.55   252.2   729.8   262.3  731.83   282.5   742.9
   292.6  749.19   302.7  753.16   322.8  756.57   353.1  767.81   363.2  771.04
   373.3  773.06   383.4  776.01   393.5  777.41   413.6  777.22   423.7  779.37
#Mann= 3 , 0 , 0
       0      .1       0   224.5    .045       0   239.5      .1       0
Bank Sta=224.5,239.5
XS Rating Curve= 0 ,0
Exp/Cntr=0.3,0.1

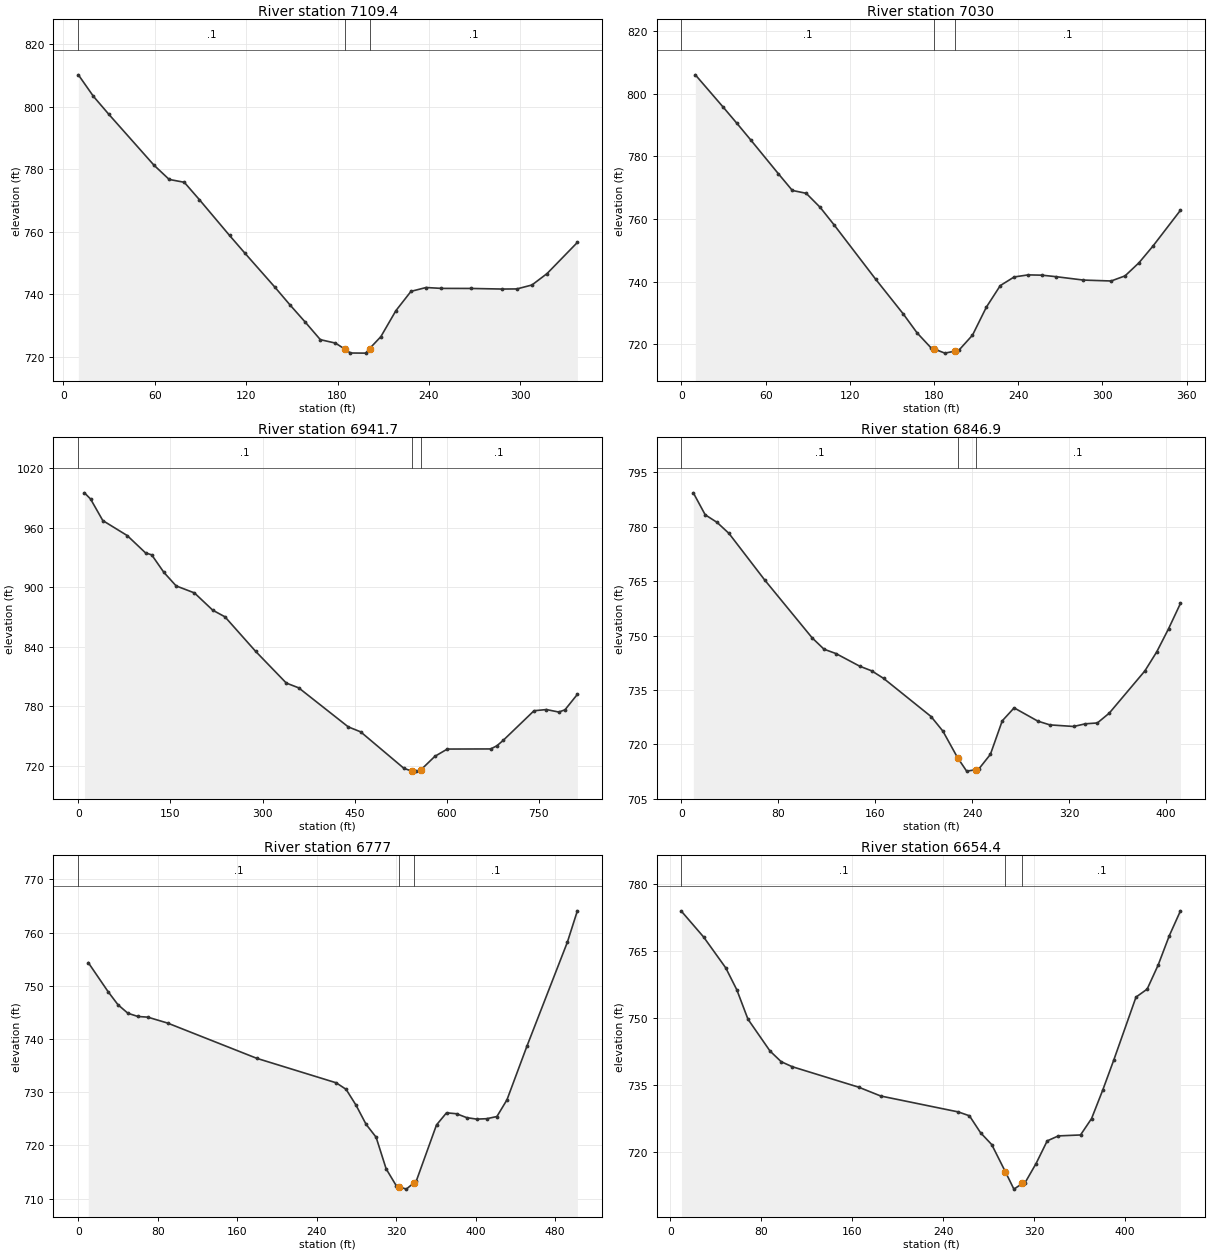
Type RM Length L Ch R = 1 ,7109.4  ,84.8,79.4,73.9
XS GIS Cut Line= 2
     1574354.953      302566.044     1574207.366      302869.417
#Sta/Elev= 29
     9.9  810.15    19.8  803.26    29.8  797.58    59.5  781.27    69.5   776.7
    79.4  775.79    89.3  770.25   109.1   758.8   119.1  753.18   138.9  742.24
   148.8  736.57   158.8  731.08   168.7  725.47   178.6  724.37  184.76  722.46
   188.5   721.2   198.5  721.16  201.02  722.61   208.4  726.41   218.3  734.74
   228.2  740.91   238.1  742.14   248.1  741.86   267.9  741.84   287.8  741.65
   297.7  741.69   307.6  742.95   317.5   746.6   337.4  756.56
#Mann= 3 , 0 , 0
     9.9      .1       0  184.76    .045       0  201.02      .1       0
Bank Sta=184.76,201.02
XS Rating Curve= 0 ,0
Exp/Cntr=0.3,0.1

Type RM Length L Ch R = 1 ,7030    ,90.5,88.4,86.2
XS GIS Cut Line= 2
     1574235.874      302528.169     1574161.227      302875.865
#Sta/Elev= 30
     9.9  806.11    29.6  795.85    39.5  790.61    49.4  785.27    69.1  774.46
      79  769.14    88.9  768.22    98.8  763.75   108.7  758.17   138.3   740.8
   158.1  729.62   167.9  723.59   177.8  718.82   180.2  718.41   187.7  717.11
   195.2  717.77   197.6  717.99   207.4  722.86   217.3  731.83   227.2  738.71
   237.1  741.47     247  742.13   256.8  742.04   266.7  741.57   286.5  740.47
   306.2  740.18   316.1  741.81     326  745.99   335.9  751.29   355.6   762.8
#Mann= 3 , 0 , 0
       0      .1       0   180.2    .045       0   195.2      .1       0
Bank Sta=180.2,195.2
XS Rating Curve= 0 ,0
Exp/Cntr=0.3,0.1

Type RM Length L Ch R = 1 ,6941.7  ,101.6,94.8,88
XS GIS Cut Line= 3
     1574326.731      302217.908      1574136.84      302460.886
     1574078.227      302961.659
#Sta/Elev= 30
     9.9  995.28    19.9  989.01    39.8  967.31    79.6  952.16   109.4   934.7
   119.4  932.73   139.3  915.03   159.2  901.41     189  894.33   218.8  876.93
   238.7  870.24   288.5  835.53   338.6  803.42   358.8   798.6   439.5  759.23
   459.6  754.25   530.2  717.39   542.9  714.65   550.4   714.6   557.9  715.98
   580.6  729.55   600.8  736.86   671.4  736.98   681.5  740.14   691.6  745.49
     742   775.5   762.2  776.69   782.3   774.2   792.4  776.44   812.6  792.03
#Mann= 3 , 0 , 0
       0      .1       0   542.9    .045       0   557.9      .1       0
Bank Sta=542.9,557.9
XS Rating Curve= 0 ,0
Exp/Cntr=0.3,0.1

Type RM Length L Ch R = 1 ,6846.9  ,75.7,69.9,64.1
XS GIS Cut Line= 3
     1574042.355      302463.553     1573998.284      302603.965
     1574046.455      302864.293
#Sta/Elev= 30
     9.8  789.39    19.6  783.33    29.4  781.23    39.2   778.2    68.7  765.35
   107.9  749.37   117.7  746.24   127.5  745.05   147.2  741.55     157  740.28
   166.8  738.21     206  727.68   215.8  723.65   227.9  716.33   235.4  712.61
   242.9  712.98   245.2   713.1     255  717.23   264.8  726.49   274.6  730.06
   294.2   726.4   304.1  725.37   323.7  724.93   333.5  725.67   343.3   725.9
   353.1   728.6   382.5  740.25   392.3  745.51   402.1  751.91   411.9  758.89
#Mann= 3 , 0 , 0
       0      .1       0   227.9    .045       0   242.9      .1       0
Bank Sta=227.9,242.9
XS Rating Curve= 0 ,0
Exp/Cntr=0.3,0.1

Type RM Length L Ch R = 1 ,6777    ,126.7,122.6,118.5
XS GIS Cut Line= 3
     1573691.836      302517.873      1573926.54       302669.56
     1574020.832      302871.467
#Sta/Elev= 30
      10  754.37    29.9  748.92    39.9  746.45    49.9  744.85    59.9  744.25
    69.9  744.12    89.8  743.01   179.6  736.38   259.5  731.78   269.5  730.55
   279.5  727.57   289.6  723.98   299.7  721.55   309.8  715.61     320  712.43
   322.6  712.26   330.1  711.79   337.6  712.94   340.2  713.34   360.5  723.86
   370.6  726.14   380.7  725.96   390.9  725.23     401  724.95   411.1  725.03
   421.3  725.44   431.4  728.57   451.6   738.7   492.2   758.2   502.3  764.11
#Mann= 3 , 0 , 0
       0      .1       0   322.6    .045       0   337.6      .1       0
Bank Sta=322.6,337.6
XS Rating Curve= 0 ,0
Exp/Cntr=0.3,0.1

Type RM Length L Ch R = 1 ,6654.4  ,56.7,55.5,54.4
XS GIS Cut Line= 3
     1573648.789      302572.193       1573809.7       302727.98
     1573937.814      302912.464
#Sta/Elev= 30
     9.7  773.82    29.2  768.07    48.7  761.16    58.4  756.27    68.2  749.71
    87.6   742.6    97.4  740.22   107.1   739.1   165.5  734.53     185  732.55
   253.3  728.99     263  728.13   272.8  724.34   282.6   721.7   294.6  715.63
   302.1  711.75   309.6  713.01   311.9  713.18   321.6  717.47   331.4  722.53
   341.2  723.64   360.7  723.85   370.4  727.51   380.2  733.85     390  740.63
   409.5  754.65   419.3  756.43     429  761.82   438.8  768.38   448.6  773.92
#Mann= 3 , 0 , 0
     9.7      .1       0   294.6    .045       0   309.6      .1       0
Bank Sta=294.6,309.6
XS Rating Curve= 0 ,0
Exp/Cntr=0.3,0.1