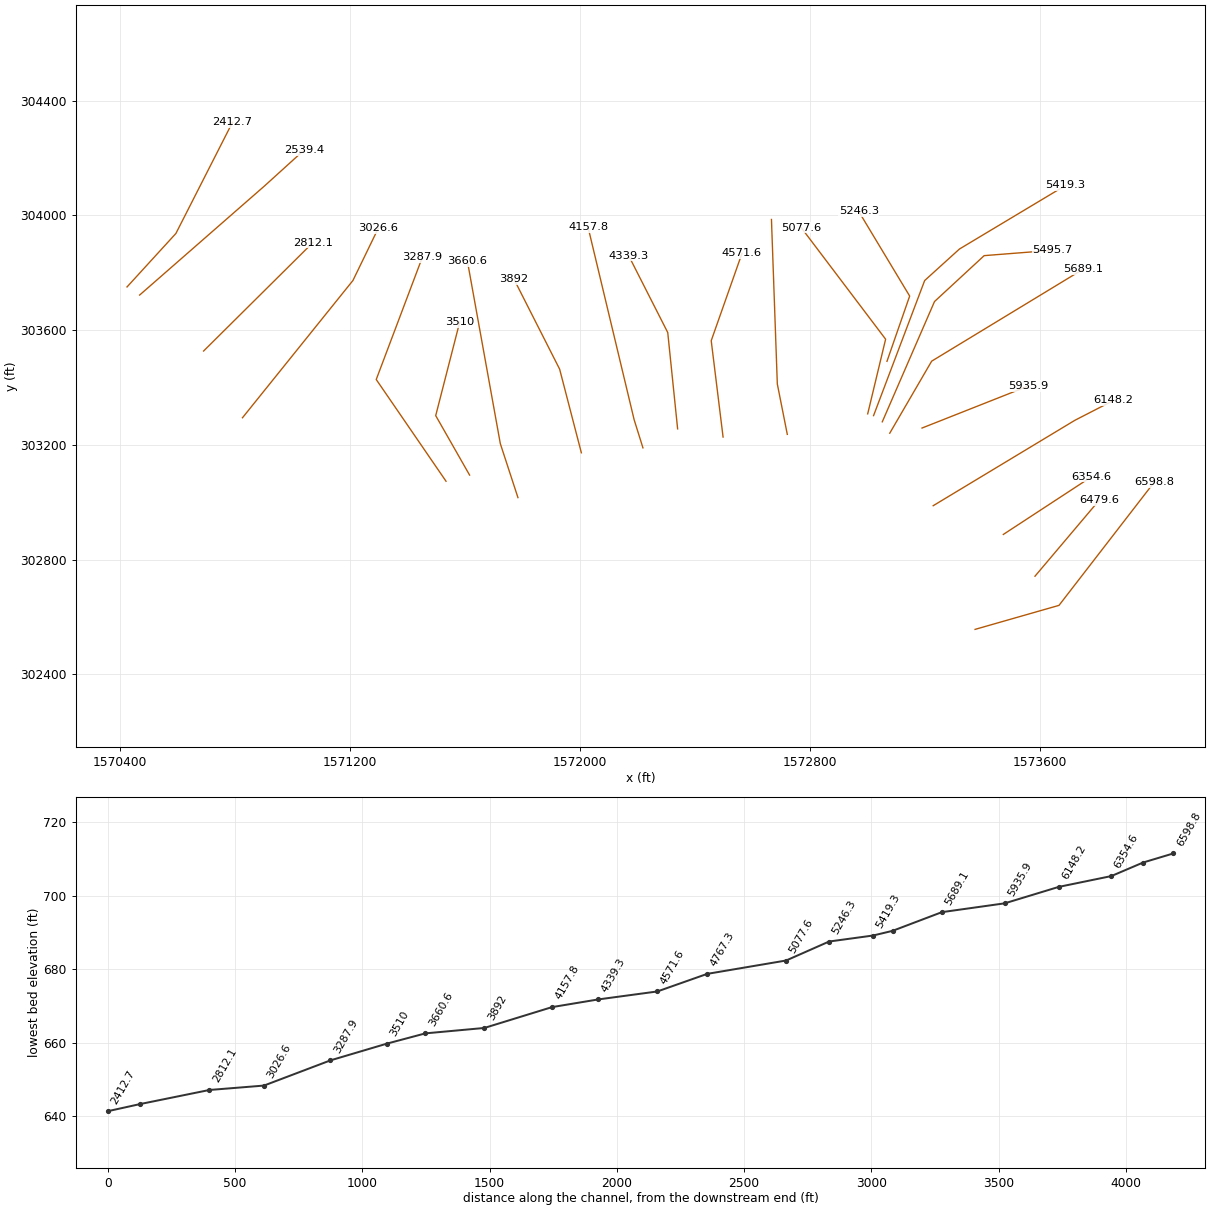
HEC-RAS study pprbrnngcr.prj: pprbrnngcr

--- pprbrnngcr.g01 (geometry) --- (continued)

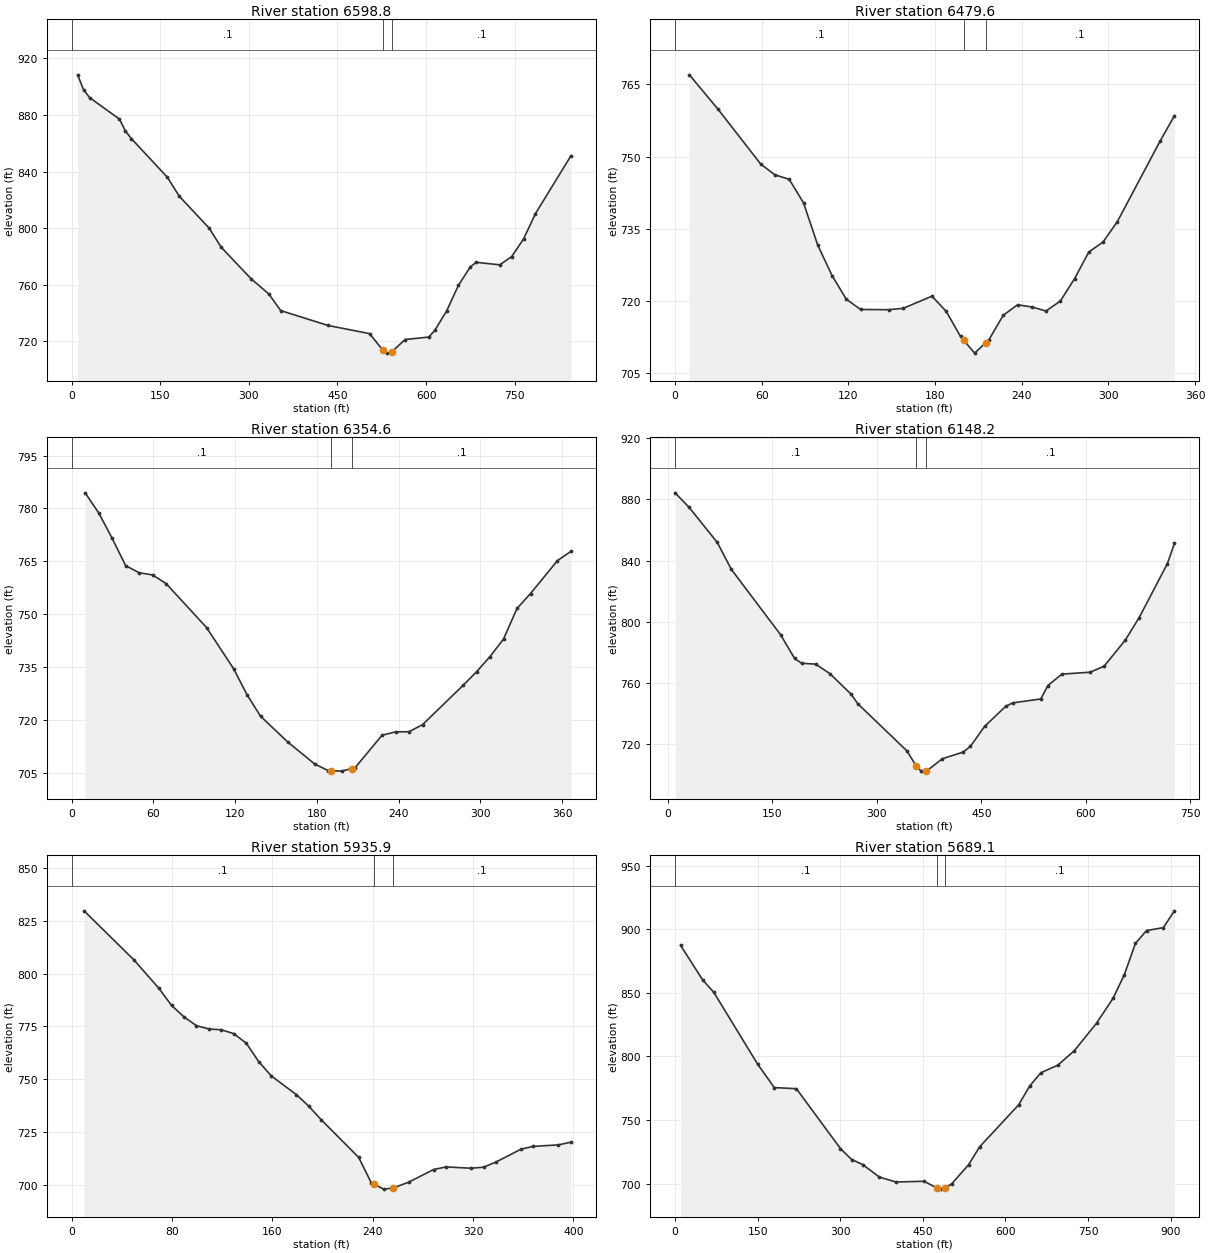
Type RM Length L Ch R = 1 ,6598.8  ,120.2,119.2,118.3
XS GIS Cut Line= 3
     1573375.236      302556.852     1573667.219      302640.567
     1573997.996      303069.352
#Sta/Elev= 30
    10.1  908.37    20.2  897.84    30.4  892.26      81  877.04    91.1  868.57
   101.2  863.23     162  835.97   182.2  822.53   232.9  799.89   253.1   786.5
   303.7  764.17   333.8  753.41   353.9  741.66   434.1  731.11   504.3  725.36
   526.9  713.61   534.4  711.56   541.9  712.49   564.5  721.19   604.6  722.93
   614.6  727.57   634.7   741.3   654.7  759.41   674.8  772.52   684.8  775.78
   724.9  774.01     745  779.88   765.1  792.36   785.1  810.18   845.3  851.17
#Mann= 3 , 0 , 0
       0      .1       0   526.9    .045       0   541.9      .1       0
Bank Sta=526.9,541.9
XS Rating Curve= 0 ,0
Exp/Cntr=0.3,0.1

Type RM Length L Ch R = 1 ,6479.6  ,131.6,125,118.5
XS GIS Cut Line= 2
     1573583.696      302742.287     1573806.654      303006.497
#Sta/Elev= 30
     9.9     767    29.6  759.89    59.3  748.42    69.1  746.18      79  745.26
    88.9  740.36    98.8  731.53   108.7   725.2   118.5  720.31   128.4  718.17
   148.2  718.12     158  718.41   177.8  720.93   187.7  717.77   197.6  712.55
   199.9  711.74   207.4  709.08   214.9   711.2   217.3  711.88   227.2  716.97
   237.1  719.14   246.9  718.69   256.8  717.85   266.7  719.92   276.6   724.6
   286.4  730.12   296.3  732.22   306.2  736.46   335.8  753.23   345.7  758.49
#Mann= 3 , 0 , 0
       0      .1       0   199.9    .045       0   214.9      .1       0
Bank Sta=199.9,214.9
XS Rating Curve= 0 ,0
Exp/Cntr=0.3,0.1

Type RM Length L Ch R = 1 ,6354.6  ,207.2,206.4,205.5
XS GIS Cut Line= 2
      1573473.53      302887.866     1573779.978      303088.748
#Sta/Elev= 30
     9.9  784.44    19.8  778.78    29.7  771.55    39.6  763.78    49.5  761.74
    59.4  761.12    69.3  758.67      99  746.17   118.8  734.51   128.7  727.09
   138.6     721   158.5  713.69   178.3  707.43   188.2  705.55   190.6  705.51
   198.1  705.39   205.6  706.13     208  706.37   227.8   715.6   237.7  716.53
   247.6  716.59   257.5   718.6   287.2  729.74   297.1  733.61     307  737.93
   316.9  742.92   326.8  751.59   336.7  755.84   356.5  765.19   366.4  767.82
#Mann= 3 , 0 , 0
       0      .1       0   190.6    .045       0   205.6      .1       0
Bank Sta=190.6,205.6
XS Rating Curve= 0 ,0
Exp/Cntr=0.3,0.1

Type RM Length L Ch R = 1 ,6148.2  ,216,212.3,208.5
XS GIS Cut Line= 3
     1573229.513      302988.068     1573722.348      303285.787
     1573857.109      303355.209
#Sta/Elev= 30
    10.1  884.36    30.3  874.84    70.7  851.92    90.9  834.31   161.6  791.64
   181.8  776.08   191.9  772.96   212.1  772.37   232.3  766.24   262.6   752.9
   272.7  746.43   343.4  715.55  356.58  705.66   363.7  702.45   371.2  702.49
     394  710.56   424.3  714.96   434.4  718.71   454.6  731.64   484.9  744.76
     495  747.06   535.4  749.61   545.5  758.34   565.7  765.87   606.1  767.09
   626.3  770.99   656.6  787.97   676.8  802.86   717.3  838.09   727.4  851.38
#Mann= 3 , 0 , 0
    10.1      .1       0  356.58    .045       0   371.2      .1       0
Bank Sta=356.58,371.2
XS Rating Curve= 0 ,0
Exp/Cntr=0.3,0.1

Type RM Length L Ch R = 1 ,5935.9  ,242.7,246.8,250.8
XS GIS Cut Line= 2
     1573190.654      303258.884     1573560.647      303405.446
#Sta/Elev= 30
     9.9  829.74    49.7  806.48    69.6  793.02    79.6  784.98    89.5  779.55
    99.5  775.37   109.4  773.81   119.4  773.41   129.3   771.6   139.3  766.99
   149.2  758.29   159.2  751.55   179.1  742.74     189  737.27     199  730.78
   228.8  712.99   238.8     701   241.2  700.27   248.7  697.98   256.2  698.51
   268.6  701.26   288.5  707.27   298.5   708.5   318.4  707.87   328.3  708.37
   338.3  710.82   358.2  716.91   368.1  718.21     388  718.94     398  720.21
#Mann= 3 , 0 , 0
       0      .1       0   241.2    .045       0   256.2      .1       0
Bank Sta=241.2,256.2
XS Rating Curve= 0 ,0
Exp/Cntr=0.3,0.1

Type RM Length L Ch R = 1 ,5689.1  ,189.2,193.4,197.7
XS GIS Cut Line= 3
     1573078.363      303240.934     1573224.141      303492.012
     1573750.934       303812.58
#Sta/Elev= 30
      10  887.48    50.1  860.25    70.1  850.64   150.2  793.77   180.2  775.53
   220.3  774.64   300.4   727.5   320.7  718.86   340.9  714.91   371.2  705.01
   401.5  701.19   452.1  701.77   474.9  696.65   482.4  695.58   489.9  696.17
   502.6  699.86     533  714.74   553.2  728.93   623.9  761.88   644.2  776.82
   664.4  787.22   694.7  793.06     725  804.48   765.5  826.21   795.8  846.02
     816  864.45   836.2  889.06   856.4  899.18   886.8  901.42     907  914.67
#Mann= 3 , 0 , 0
       0      .1       0   474.9    .045       0   489.9      .1       0
Bank Sta=474.9,489.9
XS Rating Curve= 0 ,0
Exp/Cntr=0.3,0.1

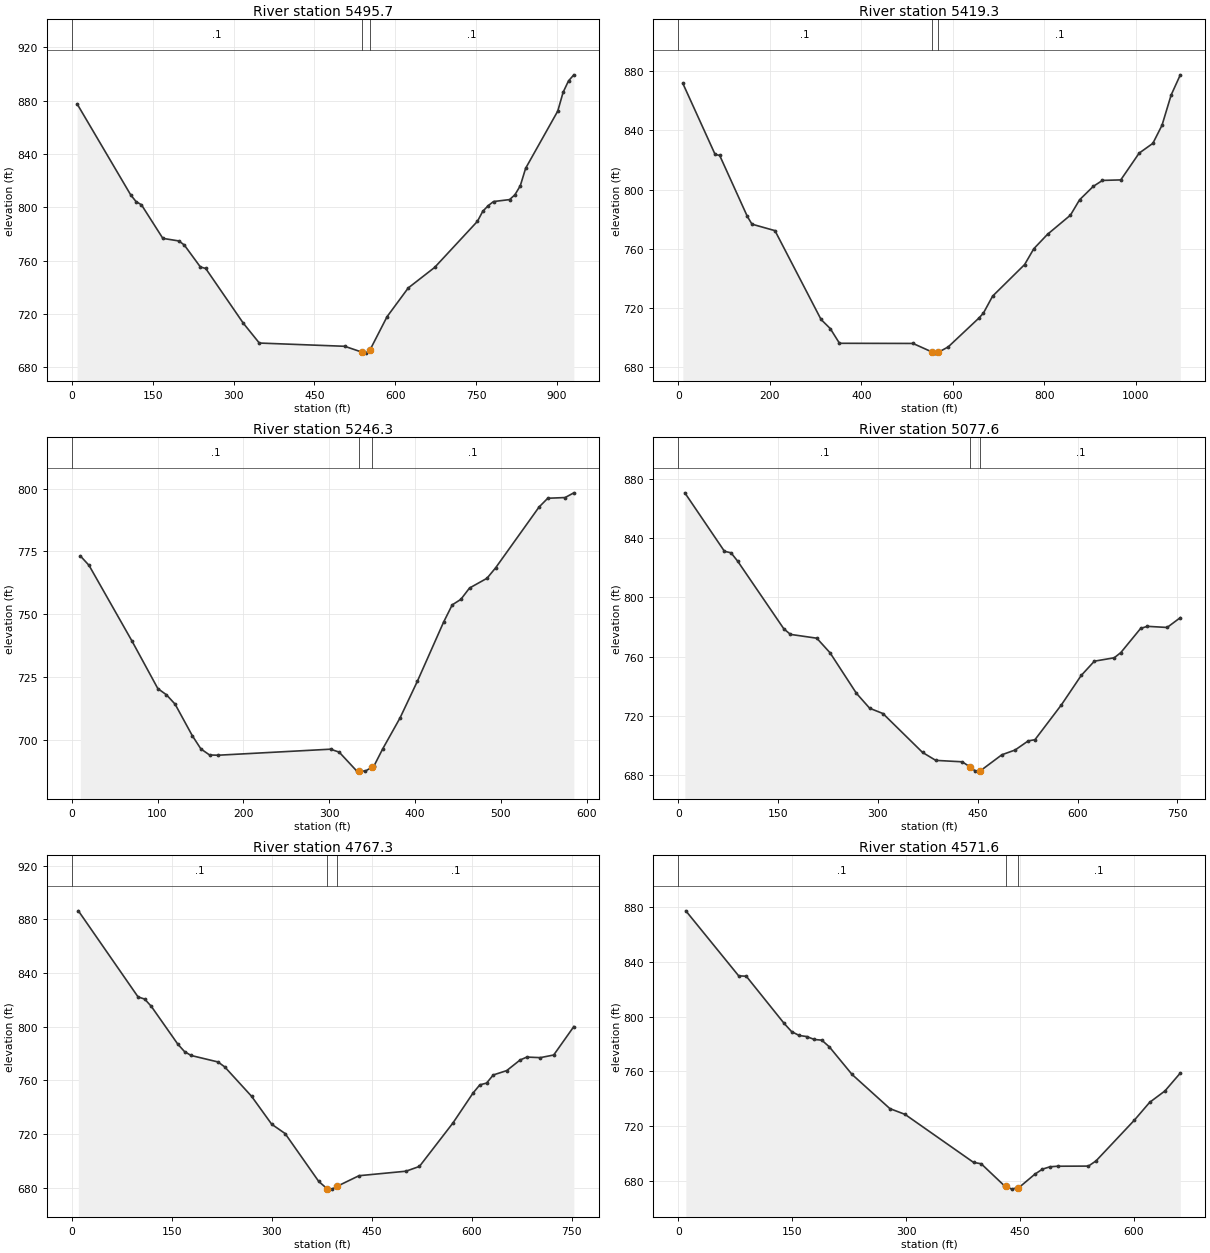
Type RM Length L Ch R = 1 ,5495.7  ,76.7,76.5,76.2
XS GIS Cut Line= 4
     1573052.329       303280.53     1573234.035      303699.927
     1573406.901      303860.025     1573644.592      303878.686
#Sta/Elev= 30
     9.9  877.55   109.3  809.25   119.2  804.23   129.2  801.83   168.9  776.63
   198.7  774.68   208.7  771.63   238.5  755.16   248.4  754.03     318  713.02
   347.8  698.07   506.2  695.63   537.9  691.27   545.4   690.5   552.9  692.76
   584.7  717.84     624  739.42     673  754.84   752.3  789.42   762.2  796.94
   772.2  801.15   782.1  804.26   811.9  805.72   821.8  809.32   831.8  816.12
   841.7  829.24   901.3  872.18   911.2  886.28   921.2  894.81   931.1  899.36
#Mann= 3 , 0 , 0
       0      .1       0   537.9    .045       0   552.9      .1       0
Bank Sta=537.9,552.9
XS Rating Curve= 0 ,0
Exp/Cntr=0.3,0.1

Type RM Length L Ch R = 1 ,5419.3  ,138.1,173,206.3
XS GIS Cut Line= 4
     1573021.999      303302.121     1573199.757      303773.097
     1573320.818      303883.055     1573689.679      304104.562
#Sta/Elev= 30
    10.1  871.85    80.5  823.84    90.6  823.08     151   781.8   161.1  776.56
   211.4  772.16   312.1  712.02   332.2  705.87   352.4  695.89     513  695.79
   553.6  690.14   561.1  689.23   568.6  689.84     590  693.45   657.3  713.04
   666.9  716.33     687  727.82     757  749.22     777  759.91     807  769.69
   857.1  782.66   877.1  793.08   907.1  802.17   927.1  806.18   967.1  806.53
  1007.2  824.65  1037.2  831.28  1057.2  843.53  1077.2  864.05  1097.2  877.68
#Mann= 3 , 0 , 0
       0      .1       0   553.6    .045       0   568.6      .1       0
Bank Sta=553.6,568.6
XS Rating Curve= 0 ,0
Exp/Cntr=0.3,0.1

Type RM Length L Ch R = 1 ,5246.3  ,166.4,168.7,171
XS GIS Cut Line= 3
      1573068.69      303491.538     1573147.608      303719.069
     1572970.298      304014.243
#Sta/Elev= 30
      10  773.23    20.1  769.48    70.2  739.35   100.3  720.45   110.4  717.95
   120.4  714.26   140.5  701.69   150.5  696.43   160.6  694.02   170.6  693.92
   301.6  696.32   311.7  695.15     332   687.7   334.6  687.67   342.1  687.59
   349.6  689.09   352.2  689.61   362.4  696.44   382.6  708.75   402.9  723.41
   433.3  746.82   443.4  753.74   453.5  755.95   463.6  760.45   483.9  764.32
     494  768.48   544.7  792.71   554.8  796.18     575  796.46   585.2  798.34
#Mann= 3 , 0 , 0
       0      .1       0   334.6    .045       0   349.6      .1       0
Bank Sta=334.6,349.6
XS Rating Curve= 0 ,0
Exp/Cntr=0.3,0.1

Type RM Length L Ch R = 1 ,5077.6  ,324.1,310.2,296.4
XS GIS Cut Line= 3
     1573001.581      303308.247     1573063.946      303568.628
     1572770.823      303956.992
#Sta/Elev= 30
     9.9  870.84    69.4  831.27    79.3  830.24    89.2  824.63   158.7  778.73
   168.6     775   208.2  772.42   228.1  762.53   267.7  735.12   287.6     725
   307.5  721.43     367  695.11   386.9  689.71   426.6  688.74     439  685.12
   446.5  682.43     454  682.68   486.2   693.5   506.1  696.73   525.9  702.92
   535.9  703.69   575.6  727.27   605.4  747.19   625.2  756.87     655  759.16
   664.9  762.67   694.7  779.04   704.7  780.46   734.5  779.69   754.3  786.33
#Mann= 3 , 0 , 0
       0      .1       0     439    .045       0     454      .1       0
Bank Sta=439,454
XS Rating Curve= 0 ,0
Exp/Cntr=0.3,0.1

Type RM Length L Ch R = 1 ,4767.3  ,204.2,195.7,187.3
XS GIS Cut Line= 3
      1572721.85      303236.783     1572687.139      303412.381
      1572666.72      303986.136
#Sta/Elev= 30
     9.9  886.46    99.4  822.24   109.4  820.59   119.3  815.18   159.1  786.95
   169.1  781.44     179  778.52   219.3  773.69   229.4  770.02   269.6  748.12
   299.9  727.22     320  720.27   370.4  684.56     383  679.09   390.5  678.79
     398  680.89   430.8   688.8   501.3  692.16   521.5  695.74   571.8   728.2
     602  750.57   612.1   756.6   622.2  757.92   632.2  763.97   652.4  767.23
   672.5  775.16   682.6  777.33   702.8  776.91   722.9  778.88   753.1  800.12
#Mann= 3 , 0 , 0
       0      .1       0     383    .045       0     398      .1       0
Bank Sta=383,398
XS Rating Curve= 0 ,0
Exp/Cntr=0.3,0.1

Type RM Length L Ch R = 1 ,4571.6  ,214,232.3,250.5
XS GIS Cut Line= 3
     1572498.371      303227.491     1572457.119      303563.402
     1572564.178      303867.882
#Sta/Elev= 30
      10   877.3    79.6   829.8    89.6  829.54   139.4  795.11   149.3  789.07
   159.3  786.24   169.2  785.47   179.2  783.32   189.1  782.82   199.1  777.87
   228.9  757.78   278.7  732.83   298.6  728.63   388.9  693.54     399  692.52
   429.2  676.64   431.8  675.97   439.3  674.01   446.8   675.1   449.4  675.48
   469.6   684.9   479.6  688.59   489.7  690.35   499.8  690.74   540.2  690.84
   550.2  694.63   600.7  724.39   620.8  737.39     641  745.75   661.2  758.81
#Mann= 3 , 0 , 0
       0      .1       0   431.8    .045       0   446.8      .1       0
Bank Sta=431.8,446.8
XS Rating Curve= 0 ,0
Exp/Cntr=0.3,0.1

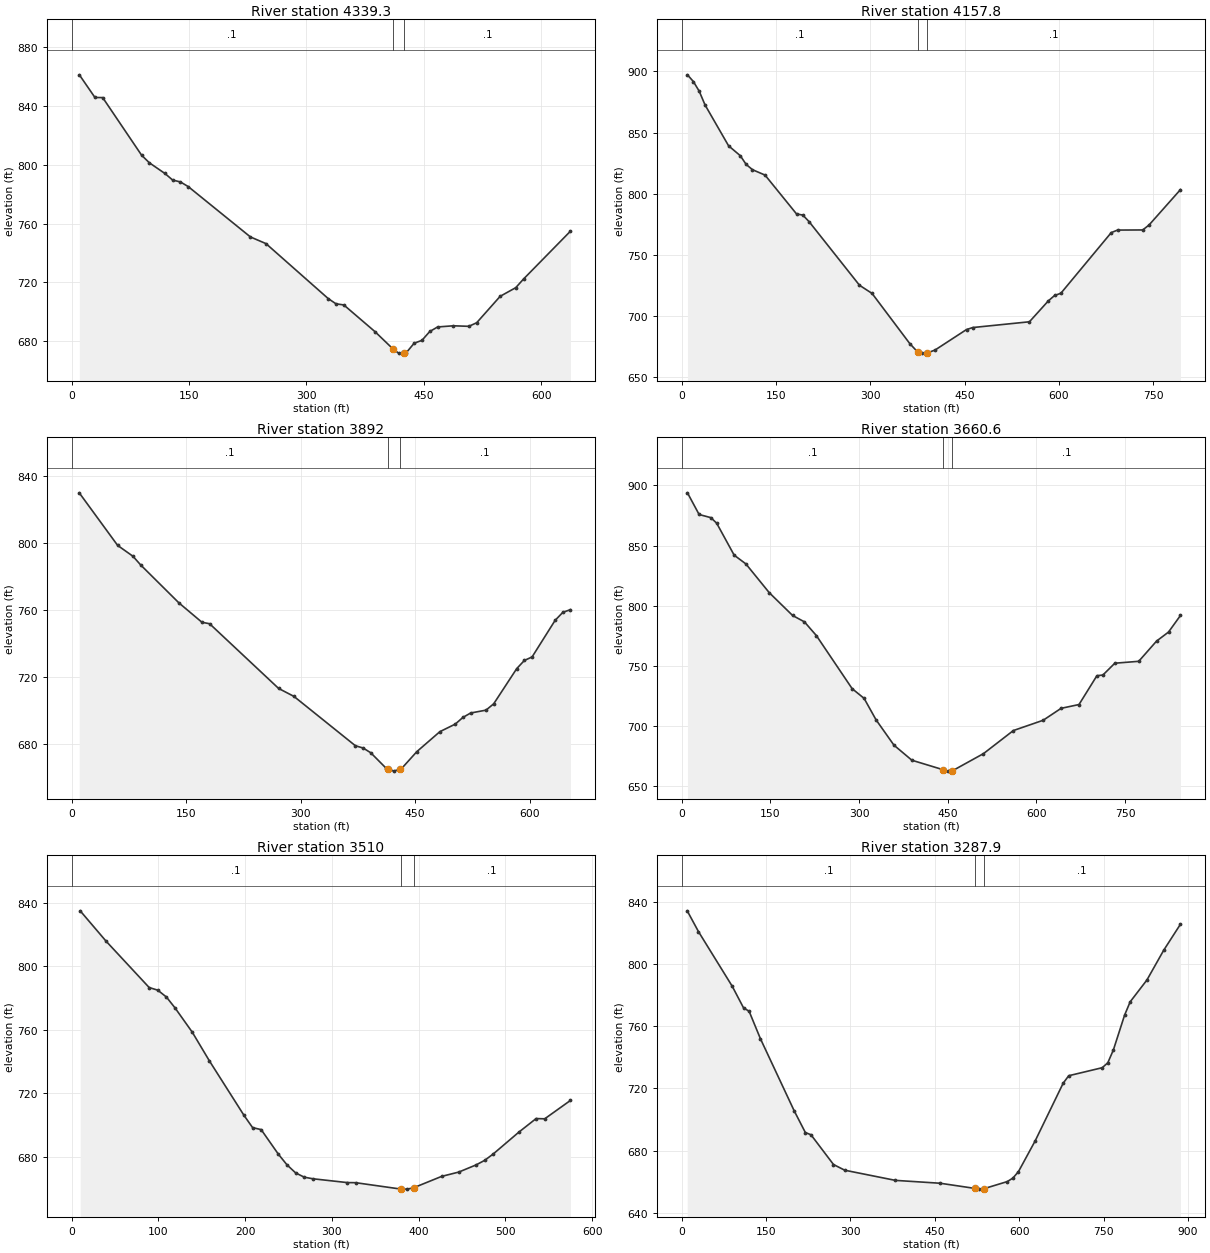
Type RM Length L Ch R = 1 ,4339.3  ,186.8,181.5,176.2
XS GIS Cut Line= 3
     1572340.238      303255.975     1572305.861      303591.885
     1572170.318      303859.042
#Sta/Elev= 30
     9.9  861.19    29.8  845.78    39.7   845.7    89.4  806.51    99.3  801.34
   119.2  794.06   129.1  789.58     139  788.32     149  785.13   228.4  750.89
   248.3  746.34   327.7  708.98   337.7  705.39   347.7  704.62   387.6  686.41
   410.1  674.88   417.6  671.84   425.1  672.08   427.5  672.16   437.5  678.56
   447.5  680.54   457.5  686.57   467.5  689.64   487.5  690.44   507.4  690.08
   517.4  692.51   547.4   710.5   567.3  716.38   577.3  722.29   637.2  754.83
#Mann= 3 , 0 , 0
       0      .1       0   410.1    .045       0   425.1      .1       0
Bank Sta=410.1,425.1
XS Rating Curve= 0 ,0
Exp/Cntr=0.3,0.1

Type RM Length L Ch R = 1 ,4157.8  ,260.7,265.8,270.9
XS GIS Cut Line= 3
     1572219.559      303189.821     1572188.931      303287.829
      1572028.46      303959.695
#Sta/Elev= 30
     9.3  897.27    18.7  891.79      28   883.9    37.3  872.63    74.7  839.25
    93.3  831.17   102.7  824.01   112.7  819.72   132.7   815.3   182.8  783.53
   192.8  782.61   202.8   777.2   282.9  725.24   302.9  718.56     363  677.48
   375.5  670.64     383  669.75   390.5   669.9     403  672.25   453.1  689.03
   463.1  690.67   553.2  695.38   583.2  712.44   593.2  716.87   603.2   718.7
   683.3  768.27   693.3  770.35   733.4  770.45   743.4  774.49   793.4  803.45
#Mann= 3 , 0 , 0
       0      .1       0   375.5    .045       0   390.5      .1       0
Bank Sta=375.5,390.5
XS Rating Curve= 0 ,0
Exp/Cntr=0.3,0.1

Type RM Length L Ch R = 1 ,3892    ,238.1,231.4,224.7
XS GIS Cut Line= 3
     1572005.309      303172.488      1571929.68        303464.2
     1571770.565      303778.502
#Sta/Elev= 30
      10  830.25    60.3  798.86    80.4  792.37    90.4  787.23   140.6  764.53
   170.8  752.95   180.8  752.09   271.2  713.46   291.3   708.7   371.8  679.24
   381.9  677.89   391.9  675.06   412.1  665.79   414.6  665.37   422.1  664.08
   429.6  665.18   432.2  665.56   452.3  675.72   482.5  687.65   502.7  692.17
   512.7  696.16   522.8  698.78   542.9  700.49     553  704.27   583.2   725.3
   593.2  730.16   603.3  732.26   633.5  754.12   643.6  758.89   653.6   760.5
#Mann= 3 , 0 , 0
       0      .1       0   414.6    .045       0   429.6      .1       0
Bank Sta=414.6,429.6
XS Rating Curve= 0 ,0
Exp/Cntr=0.3,0.1

Type RM Length L Ch R = 1 ,3660.6  ,160.3,150.6,140.9
XS GIS Cut Line= 3
     1571784.648      303016.265     1571723.393      303204.114
     1571608.941      303839.923
#Sta/Elev= 30
     9.9  893.88    29.6  875.87    49.4  873.27    59.3  868.66    88.9  842.07
   108.7  834.81   148.2  810.91   187.7  791.96   207.7  786.65   227.9  775.25
   288.4  731.13   308.6  723.07   328.8  705.26   359.1  684.18   389.4  671.67
   442.4  663.76   449.9  662.61   457.4  662.75   510.5  677.16     561  696.33
   611.4  704.88   641.7  714.79     672  717.95   702.3  741.91   712.4  742.47
   732.6  752.29     773  753.87   803.2  770.69   823.4  778.18   843.6  791.97
#Mann= 3 , 0 , 0
       0      .1       0   442.4    .045       0   457.4      .1       0
Bank Sta=442.4,457.4
XS Rating Curve= 0 ,0
Exp/Cntr=0.3,0.1

Type RM Length L Ch R = 1 ,3510    ,224.6,222.2,219.7
XS GIS Cut Line= 3
      1571616.36      303094.895     1571498.497      303302.138
     1571581.983      303628.227
#Sta/Elev= 30
     9.9  834.78    39.7  815.72    89.4  786.56    99.3   784.9   109.3  780.58
   119.2  773.76   139.1  758.47   158.9  740.38   198.7   706.2   208.6   698.5
   218.5  697.24   238.4  681.73   248.3  675.07   258.2  670.04   268.1  667.35
     278  666.35   317.6  663.95   327.5  663.87   379.4  659.87   386.9  659.83
   394.4  660.73   426.5  667.84   446.3  670.56   466.1  675.03     476  677.88
   485.9   681.9   515.6   695.7   535.4  704.19   545.3  704.03     575   715.6
#Mann= 3 , 0 , 0
       0      .1       0   379.4    .045       0   394.4      .1       0
Bank Sta=379.4,394.4
XS Rating Curve= 0 ,0
Exp/Cntr=0.3,0.1

Type RM Length L Ch R = 1 ,3287.9  ,268.6,261.3,254
XS GIS Cut Line= 3
     1571534.398      303073.375     1571291.546      303428.074
     1571452.405      303855.382
#Sta/Elev= 30
      10   834.2      30  820.81      90  785.68     110  771.85     120   769.6
     140  752.03   199.9  705.74   219.9  691.66   229.9  690.22   269.9   671.1
   289.9  667.43   379.9   660.9   459.6  659.05   521.6  655.71   529.1  655.27
   536.6  655.48   578.8  660.13   588.7  662.37   598.6  666.52   628.4  686.36
     678  723.33   687.9  728.18   747.5  733.34   757.4  736.52   767.3  744.79
   787.2  767.14   797.1   775.7   826.9  789.74   856.7  808.86   886.5  825.61
#Mann= 3 , 0 , 0
       0      .1       0   521.6    .045       0   536.6      .1       0
Bank Sta=521.6,536.6
XS Rating Curve= 0 ,0
Exp/Cntr=0.3,0.1

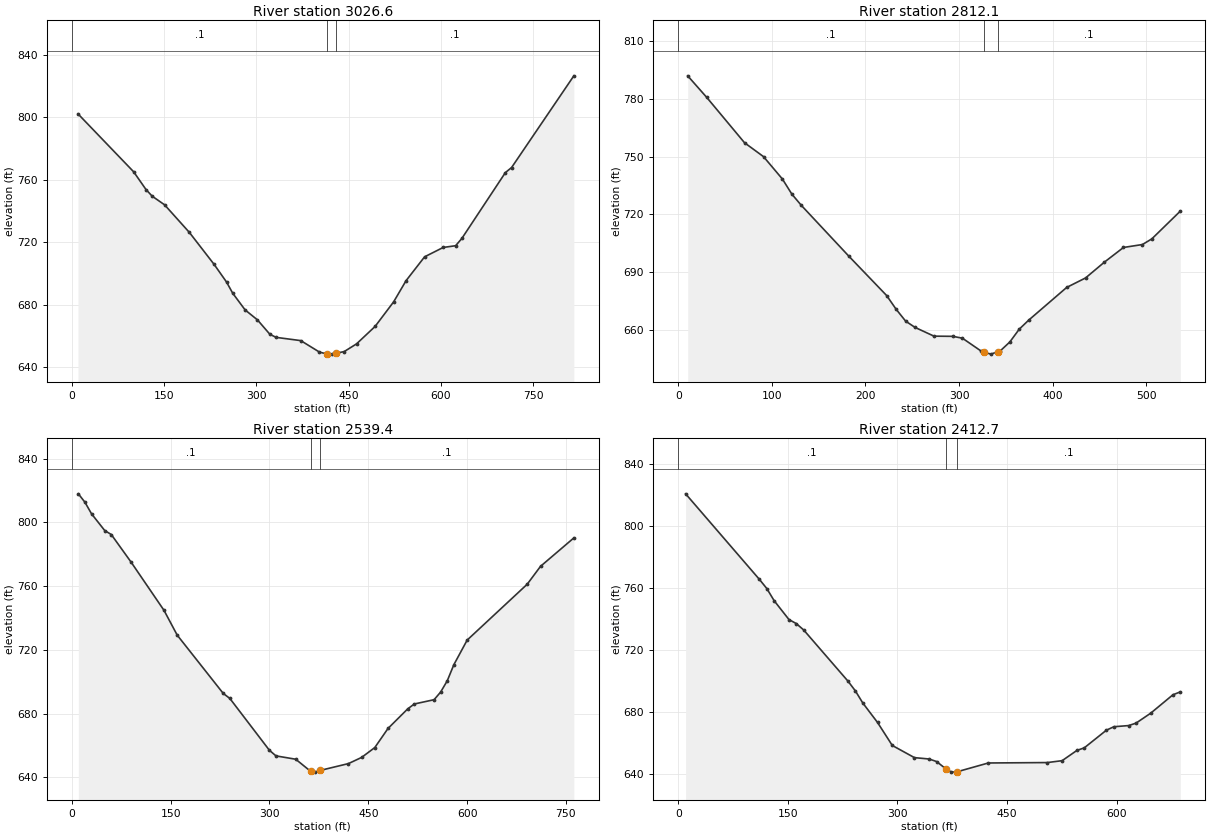
Type RM Length L Ch R = 1 ,3026.6  ,217.1,214.5,211.9
XS GIS Cut Line= 3
     1570826.185      303294.756     1571210.526      303773.389
     1571298.692      303955.508
#Sta/Elev= 30
    10.1  802.15   100.6  765.08   120.8  753.66   130.8  749.45   150.9  743.95
   191.2  726.28   231.5  705.79   251.6  694.54   261.6  687.41   281.8   676.7
   301.9  670.31     322  661.13   332.1  659.14   372.3  657.05   402.5  649.75
   415.1  648.44   422.6  648.41   430.1  649.04   442.8  650.02   462.9  654.96
   493.1  666.13   523.3  681.89   543.4  695.39   573.6  710.68   603.8  716.67
     624  717.78   634.1  722.42   704.9  764.57     715  767.82   816.2  826.49
#Mann= 3 , 0 , 0
       0      .1       0   415.1    .045       0   430.1      .1       0
Bank Sta=415.1,430.1
XS Rating Curve= 0 ,0
Exp/Cntr=0.3,0.1

Type RM Length L Ch R = 1 ,2812.1  ,274.1,272.7,271.2
XS GIS Cut Line= 2
     1570690.896       303527.41     1571071.138      303905.603
#Sta/Elev= 30
    10.1  792.12    30.4  780.91    70.8  757.28    91.1  750.04   111.3  738.36
   121.4   730.5   131.5  724.66   182.1  698.28   222.6  677.72   232.7  670.61
   242.9  664.39     253  661.11   273.2  656.57   293.4  656.47   303.6  655.49
   323.8  648.71   326.4  648.32   333.9  647.21   341.4  648.47     344  648.91
   354.2  653.54   364.3  660.23   374.4  664.93   414.9  681.93   435.1  686.88
   455.3  695.14   475.6  702.75   495.8  704.27   505.9  707.23   536.3  721.67
#Mann= 3 , 0 , 0
       0      .1       0   326.4    .045       0   341.4      .1       0
Bank Sta=326.4,341.4
XS Rating Curve= 0 ,0
Exp/Cntr=0.3,0.1

Type RM Length L Ch R = 1 ,2539.4  ,118.1,126.8,135.4
XS GIS Cut Line= 3
     1570468.357      303722.577     1570904.618      304104.562
     1571039.379      304227.072
#Sta/Elev= 30
      10  817.96      20  812.68      30  805.42      50  794.94      60  792.41
      90  775.14     140  744.85     160  729.32   229.9  692.74   239.9   689.6
   299.9   657.1   309.9  653.56   339.9  651.46   362.4  643.92   369.9  643.37
   377.4  644.48   419.9  648.72   439.9   652.6   459.9  658.78   479.9  670.74
   509.9  683.07   519.9  686.12   549.9  688.81   559.9  693.64   569.9   700.7
   579.9  710.77   600.1  726.21   691.2  761.24   711.4  772.46     762   790.3
#Mann= 3 , 0 , 0
       0      .1       0   362.4    .045       0   377.4      .1       0
Bank Sta=362.4,377.4
XS Rating Curve= 0 ,0
Exp/Cntr=0.3,0.1

Type RM Length L Ch R = 1 ,2412.7  ,174.9,177.6,180.2
XS GIS Cut Line= 3
     1570424.419      303750.841     1570594.555      303937.375
     1570791.337      304324.791
#Sta/Elev= 30
    10.1  820.95   111.1  765.74   121.2  759.86   131.3  751.97   151.5  739.85
   161.6  737.23   171.7  733.11   232.3   700.1   242.4  693.82   252.5  686.05
   272.7  673.47   292.9  658.63   323.2  650.78   343.4  649.89   353.5  648.26
   366.2  643.55   373.7  641.43   381.2  641.61   424.3  647.33   505.1   647.6
   525.3  648.82   545.5  655.43   555.6  657.09   585.9   668.5   596.1  670.71
   616.3  671.46   626.4  673.03   646.6  679.49   676.9  691.33     687  693.19
#Mann= 3 , 0 , 0
       0      .1       0   366.2    .045       0   381.2      .1       0
Bank Sta=366.2,381.2
XS Rating Curve= 0 ,0
Exp/Cntr=0.3,0.1