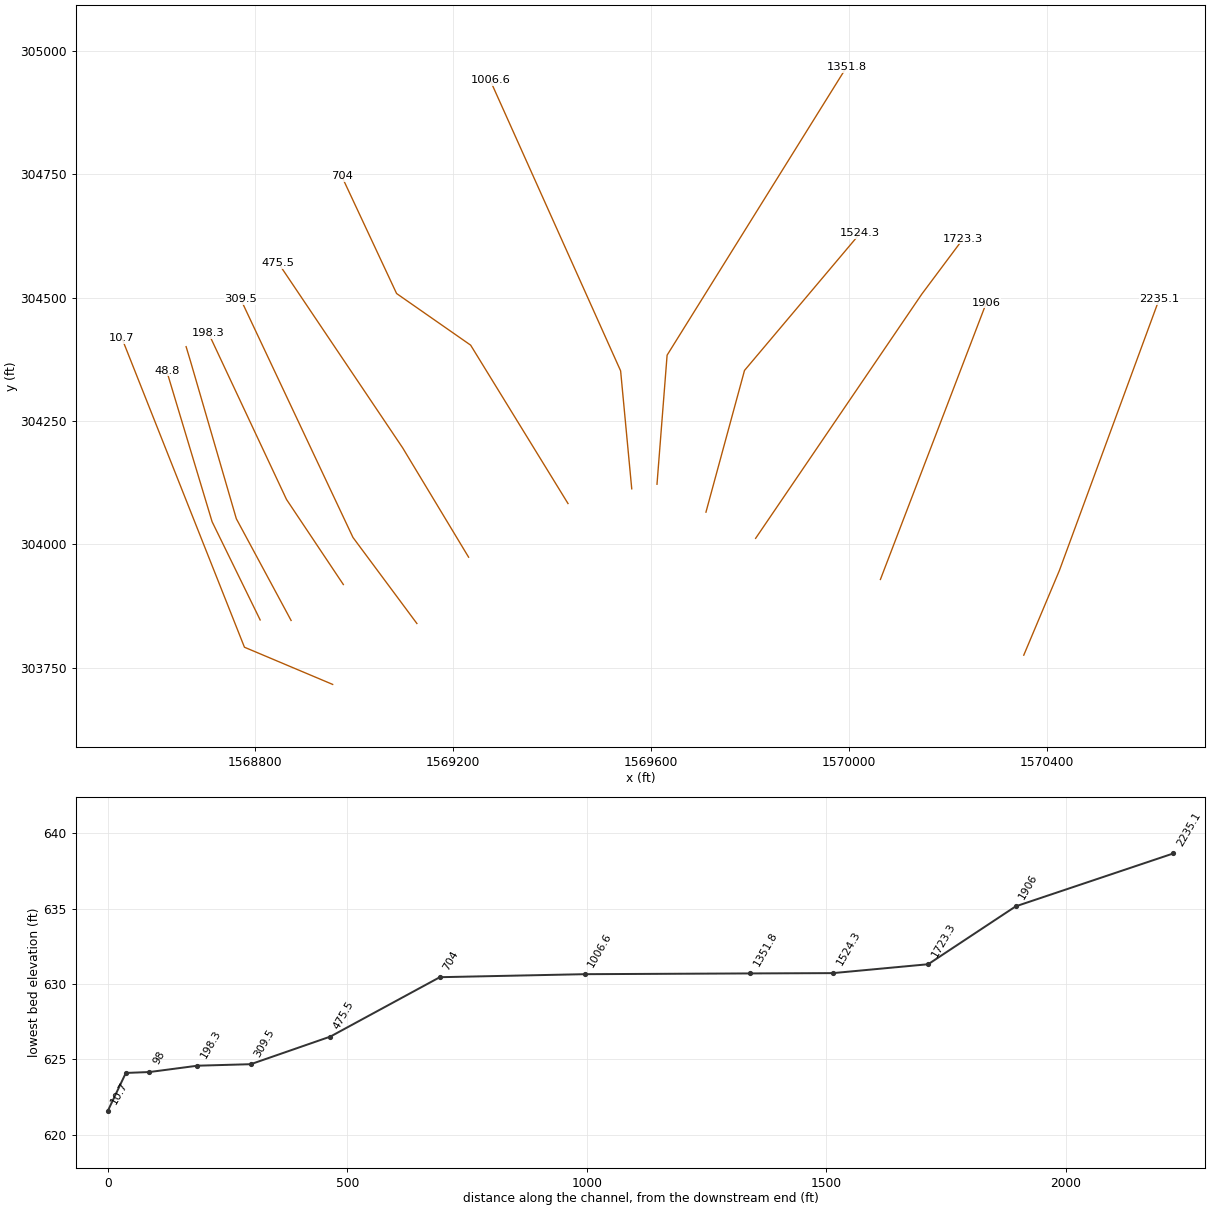
HEC-RAS study pprbrnngcr.prj: pprbrnngcr

--- pprbrnngcr.g01 (geometry) --- (continued)

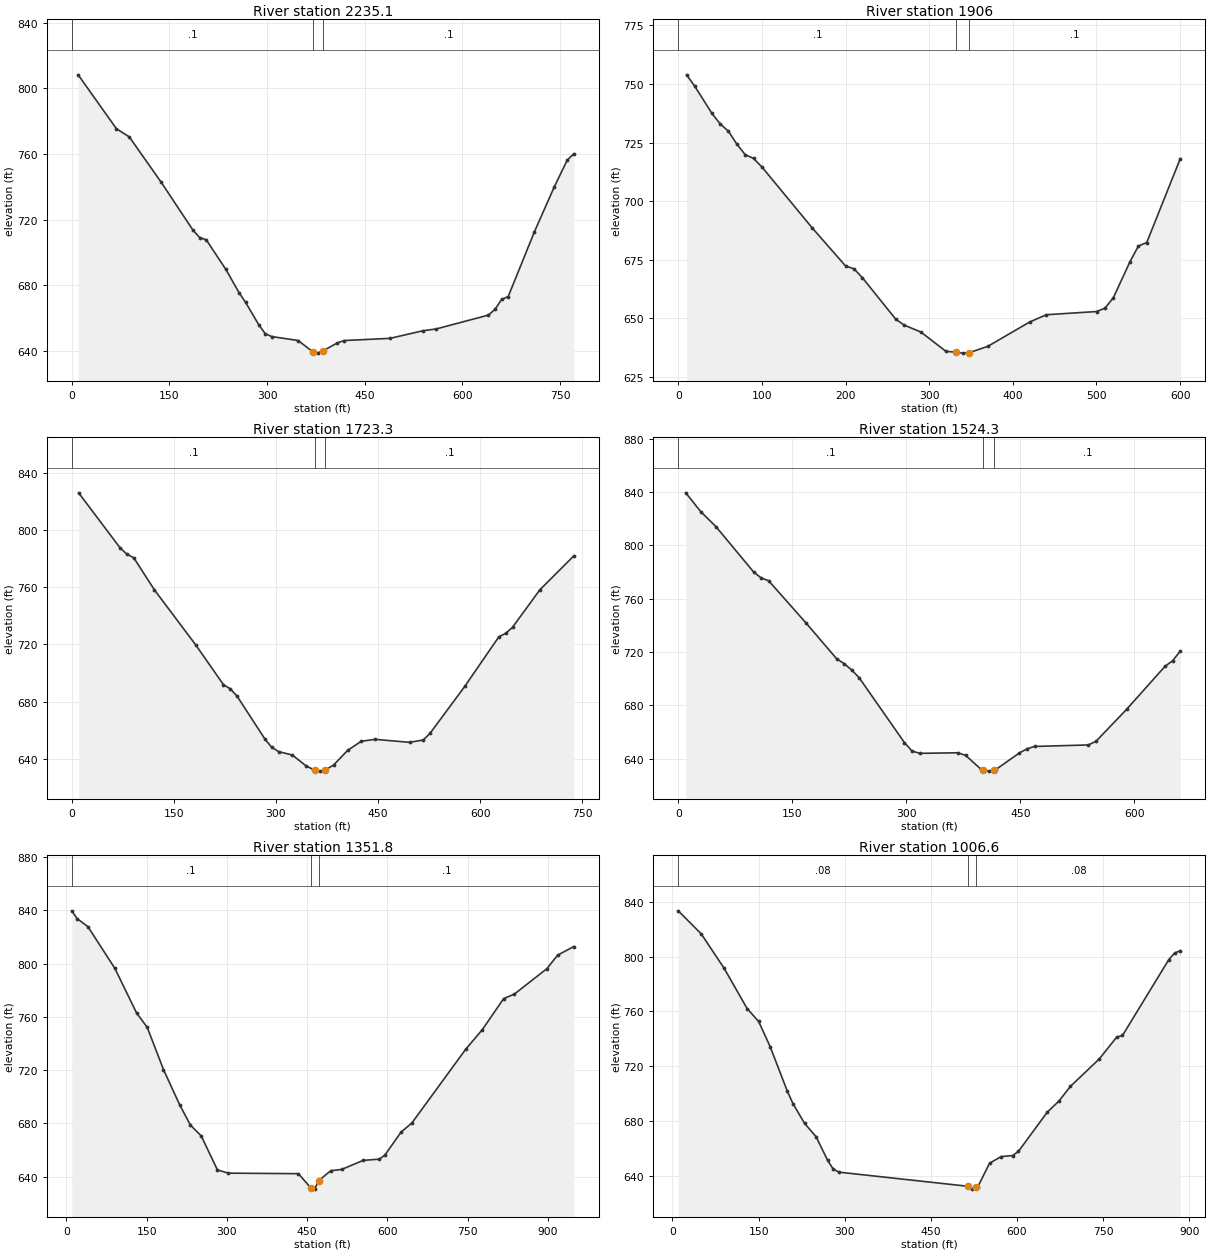
Type RM Length L Ch R = 1 ,2235.1  ,329.4,329.1,328.8
XS GIS Cut Line= 3
     1570353.323      303775.827     1570425.444      303947.624
     1570626.929      304496.594
#Sta/Elev= 30
     9.8  808.17    68.6  775.33    88.3  770.38   137.3  742.76   186.3  713.48
   196.4  709.07   206.5  707.71   236.7  689.62   256.9  675.49     267  669.56
   287.1  655.98   297.2  650.49   307.3  648.74   347.6  646.35   370.4   639.4
   377.9  638.66   385.4  639.97   408.1  644.91   418.2  646.33   488.8  647.66
   539.2  652.28   559.4  653.36     640  661.84   650.1  665.38   660.2  671.34
   670.3  673.13   710.6  712.61   740.9   739.8     761  756.27   771.1  760.08
#Mann= 3 , 0 , 0
       0      .1       0   370.4    .045       0   385.4      .1       0
Bank Sta=370.4,385.4
XS Rating Curve= 0 ,0
Exp/Cntr=0.3,0.1

Type RM Length L Ch R = 1 ,1906    ,187.9,182.7,177.5
XS GIS Cut Line= 2
     1570063.651      303929.176     1570277.857      304489.802
#Sta/Elev= 30
      10  753.89      20  748.91      40  737.57      50  733.01      60  729.85
      70  724.33      80  719.85      90  718.22     100  714.59     160  688.65
   200.1  672.31   210.1  671.13   220.1  667.34   260.1   649.6   270.1  647.12
   290.1  644.14   320.1   635.9   332.6  635.56   340.1  635.15   347.6   635.3
   370.1  638.05   420.1  648.43   440.1  651.53   500.1   652.9   510.1  654.32
   520.1  658.76   540.1  674.21   550.1  680.84   560.1  682.35   600.2  718.17
#Mann= 3 , 0 , 0
       0      .1       0   332.6    .045       0   347.6      .1       0
Bank Sta=332.6,347.6
XS Rating Curve= 0 ,0
Exp/Cntr=0.3,0.1

Type RM Length L Ch R = 1 ,1723.3  ,201.3,199,196.7
XS GIS Cut Line= 3
     1569811.469      304012.466     1570147.098      304506.803
     1570230.813      304619.104
#Sta/Elev= 30
    10.1  826.13    70.9  787.64      81  783.17    91.1  780.65   121.5  758.13
   182.3  719.54   222.8  691.87   232.9  688.91   243.1  683.64   283.6  653.88
   293.7  648.04   303.8  644.97   324.1  642.56   344.3  634.97   357.1  631.88
   364.6  631.31   372.1  632.01   384.8  635.63   405.1  645.77   425.3  652.21
   445.6  653.56   496.2  651.46   516.5  653.13   526.6  657.95   577.3  690.58
   627.5  725.38   637.5  727.73   647.5  731.99   687.6  758.21   737.6  782.01
#Mann= 3 , 0 , 0
       0      .1       0   357.1    .045       0   372.1      .1       0
Bank Sta=357.1,372.1
XS Rating Curve= 0 ,0
Exp/Cntr=0.3,0.1

Type RM Length L Ch R = 1 ,1524.3  ,169.1,172.5,175.9
XS GIS Cut Line= 3
     1569711.081      304065.489     1569788.975      304352.464
     1570022.654      304630.215
#Sta/Elev= 30
     9.9  839.38    29.7  825.22    49.6  814.05    99.1  780.08     109  775.61
   118.9  773.45   168.5  741.52   208.2  715.04   218.1  711.34     228  706.59
   237.9  700.81   297.4  652.18   307.4  645.84   317.5  644.07   367.9  644.47
     378  642.51   398.2  632.11   400.8  631.75   408.3  630.72   415.8  631.82
   418.4  632.21   448.6  644.32   458.7  647.44   468.8  649.22   539.3  650.36
   549.4  653.06   589.8  677.13   640.2  709.31   650.3  713.53   660.3  720.81
#Mann= 3 , 0 , 0
       0      .1       0   400.8    .045       0   415.8      .1       0
Bank Sta=400.8,415.8
XS Rating Curve= 0 ,0
Exp/Cntr=0.3,0.1

Type RM Length L Ch R = 1 ,1351.8  ,323.1,345.2,367.4
XS GIS Cut Line= 3
     1569612.137      304122.034     1569632.556      304383.388
     1569994.982      304966.385
#Sta/Elev= 30
    10.1  839.53    20.2  833.66    40.3  827.64    90.7  796.32   131.1     763
   151.2  752.05   181.5  720.45   211.7  694.06   231.9  678.73   252.1  670.62
   282.3  645.16   302.5  642.69   433.8  642.29   456.6  631.77   464.1   630.7
   471.6  637.07   494.3  644.54   514.5  645.46   554.9  652.27   585.2  653.21
   595.3   656.2   625.6  673.46   645.8  680.31   746.7  735.78     777   750.1
   817.4  773.67   837.6  777.09   898.1   796.1   918.3  806.26   948.6  812.76
#Mann= 3 , 0 , 0
    10.1      .1       0   456.6    .045       0   471.6      .1       0
Bank Sta=456.6,471.6
XS Rating Curve= 0 ,0
Exp/Cntr=0.3,0.1

Type RM Length L Ch R = 1 ,1006.6  ,290.3,302.5,314.8
XS GIS Cut Line= 3
     1569561.091       304112.73     1569538.631      304351.624
     1569275.235      304939.672
#Sta/Elev= 30
      10  833.25      50  816.49      90  791.38     130  762.07     150  752.73
     170  734.44     200  701.94     210  692.73     230  678.51     250  668.84
   270.2  651.59   280.2  645.02   290.3  642.99   514.3  632.73   521.8  630.65
   529.3  632.18   531.9   632.5   552.1  649.51   572.2  654.32   592.3   655.1
   602.4  658.12   652.7  686.71   672.9  694.74     693  705.48   743.3  725.45
   773.5  741.32   783.6  742.49   864.2  797.69   874.2  802.45   884.3  804.24
#Mann= 3 , 0 , 0
      10     .08       0   514.3    .045       0   529.3     .08       0
Bank Sta=514.3,529.3
XS Rating Curve= 0 ,0
Exp/Cntr=0.3,0.1

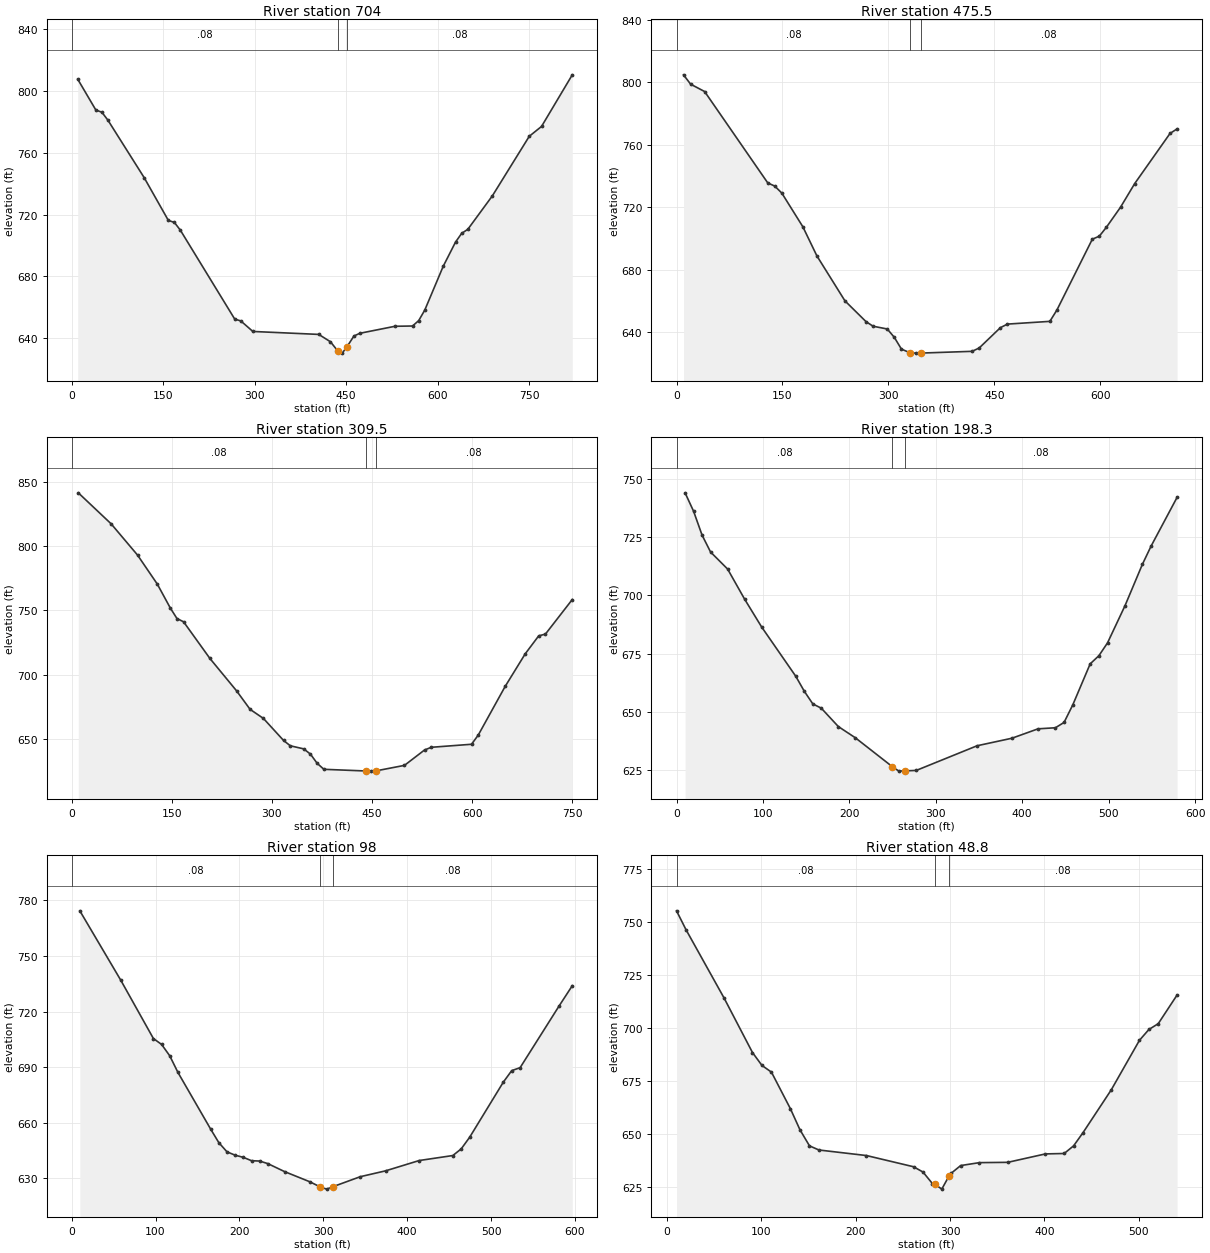
Type RM Length L Ch R = 1 ,704     ,238.8,228.5,217.9
XS GIS Cut Line= 4
     1569432.306      304082.912     1569235.522      304403.709
     1569085.886       304508.25     1568975.085      304745.698
#Sta/Elev= 30
     9.9  807.47    39.6  787.56    49.5  786.13    59.4  780.99   118.8  743.89
   158.5  716.22   168.4  714.91   178.3  709.84   267.4  652.41   277.3  651.27
   297.1  644.45   405.2  642.55   424.4  637.77   436.1  631.97   443.6  630.45
   451.1  634.37   462.8  641.49   472.4  643.26   530.1   647.8   558.9  647.98
     569  651.44     579  658.26   609.3  686.62   629.4  702.18   639.5  707.85
   649.6  710.47   689.9  732.12   750.4   770.6   770.5  776.95   820.9   810.3
#Mann= 3 , 0 , 0
       0     .08       0   436.1    .045       0   451.1     .08       0
Bank Sta=436.1,451.1
XS Rating Curve= 0 ,0
Exp/Cntr=0.3,0.1

Type RM Length L Ch R = 1 ,475.5   ,167.1,166,169.3
XS GIS Cut Line= 3
     1569231.423      303974.271     1569098.184      304195.652
     1568847.081      304569.745
#Sta/Elev= 30
     9.9  804.79    19.9  798.82    39.8  794.08   129.2  735.55   139.1  733.51
   149.1  729.04   178.9  707.45   198.8  688.78   238.5     660   268.4  646.66
   278.4  643.74   298.4  641.97   308.4  636.64   318.5  629.08     331  626.68
   338.5  626.51     346  626.54   418.6  627.66   428.6   629.8   458.6  642.81
   468.6  645.11   528.7  646.86   538.7  654.15   588.8  699.48   598.8  701.46
   608.8  707.17   628.8  720.01   648.9  735.17   698.9  767.26   708.9  770.17
#Mann= 3 , 0 , 0
       0     .08       0     331    .045       0     346     .08       0
Bank Sta=331,346
XS Rating Curve= 0 ,0
Exp/Cntr=0.3,0.1

Type RM Length L Ch R = 1 ,309.5   ,112.4,111.2,105.2
XS GIS Cut Line= 3
     1569126.882      303840.008     1568997.743      304014.243
     1568770.902      304496.594
#Sta/Elev= 30
     9.9  841.74    59.1  817.55    98.6   793.2   128.2   770.6   147.9  751.74
   157.7   743.7   167.6  741.15     207  712.59     247   687.3   267.2  672.88
   287.3  665.74   317.4  648.59   327.5  644.44   347.6  642.03   357.7  637.92
   367.7  630.77   377.8   626.1   440.7  624.79   448.2  624.68   455.7  624.87
   498.5  629.17   528.6  641.18   538.7  643.27     599  645.63   609.1  652.86
   649.3  690.71   679.5  716.25   699.6  730.19   709.7  731.57   749.9  758.53
#Mann= 3 , 0 , 0
       0     .08       0   440.7    .045       0   455.7     .08       0
Bank Sta=440.7,455.7
XS Rating Curve= 0 ,0
Exp/Cntr=0.3,0.1

Type RM Length L Ch R = 1 ,198.3   ,103.8,100.2,96.6
XS GIS Cut Line= 3
      1568978.27      303918.926      1568863.48      304091.111
     1568705.644      304428.307
#Sta/Elev= 30
     9.9     744    19.7  736.13    29.6  725.81    39.4   718.6    59.1   711.3
    78.8  698.36    98.5  686.42     138  665.27   147.8  658.88   157.7  653.42
   167.5  651.59   187.2  643.71   206.9  638.89   249.8  626.46   257.3  624.58
   264.8   624.7   277.4  624.88   347.8  635.47   388.1   638.7   418.3  642.73
   438.4  643.19   448.4  645.48   458.5  653.02   478.6  670.61   488.7  674.11
   498.7  679.63   518.9  695.56     539   713.3   549.1  721.15   579.2  742.09
#Mann= 3 , 0 , 0
       0     .08       0   249.8    .045       0   264.8     .08       0
Bank Sta=249.8,264.8
XS Rating Curve= 0 ,0
Exp/Cntr=0.3,0.1

Type RM Length L Ch R = 1 ,98      ,49.1,49.3,49.5
XS GIS Cut Line= 4
     1568872.704      303846.158     1568762.014      304052.165
     1568669.772      304369.887     1568660.548      304400.634
#Sta/Elev= 30
     9.7  774.41    58.5  736.96    97.4  705.47   107.2  702.27   116.9  696.13
   126.7  687.13   165.7  656.53   175.4  649.26   185.1  644.31   194.9  642.47
   204.6  641.32   214.4   639.5   224.1  639.32   233.9  637.92   253.9   633.6
     284  628.11   296.5  625.29     304  624.16   311.5  625.48   344.1  630.88
   374.2  634.03   414.3   639.6   454.4   642.3   464.4   645.9   474.5   652.2
   514.6  681.94   524.6  688.14   534.6  689.73   580.8  722.85   596.8  733.99
#Mann= 3 , 0 , 0
       0     .08       0   296.5    .045       0   311.5     .08       0
Bank Sta=296.5,311.5
XS Rating Curve= 0 ,0
Exp/Cntr=0.3,0.1

Type RM Length L Ch R = 1 ,48.8    ,36.1,38,39.9
XS GIS Cut Line= 3
     1568810.184      303847.182     1568713.046      304046.157
     1568621.198      304351.828
#Sta/Elev= 30
    10.1   755.3    20.1  746.44    60.4  714.27    90.6  688.49   100.6  682.43
   110.7  679.25   130.8  661.99   140.9  652.09     151   644.5     161  642.55
   211.4  639.93   261.3  634.65   271.3  632.15   281.3   626.7   283.7  626.48
   291.2   624.1   298.7  630.13   301.2  631.58   311.2  635.21   331.1  636.59
   361.1  636.73     401   640.7   420.9   640.9   430.9   644.5   440.9  650.74
   470.8   670.9   500.7  694.27   510.7  699.36   520.6   702.1   540.6  715.64
#Mann= 3 , 0 , 0
    10.1     .08       0   283.7    .045       0   298.7     .08       0
Bank Sta=283.7,298.7
XS Rating Curve= 0 ,0
Exp/Cntr=0.3,0.1

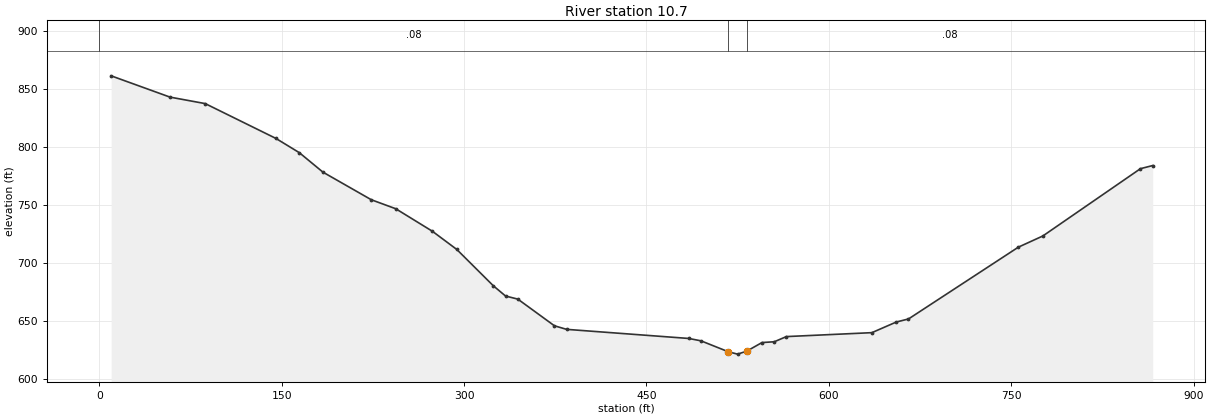
Type RM Length L Ch R = 1 ,10.7    ,13.5,10.7,8
XS GIS Cut Line= 3
     1568956.709      303716.614     1568778.428       303791.94
     1568530.847      304417.559
#Sta/Elev= 30
     9.7  861.51    58.1  843.16    87.1  837.56   145.2  807.56   164.5  795.24
   183.9  778.47   223.7  754.66   243.8  746.91   273.9  727.51     294  711.81
   324.1  680.43   334.1  671.66   344.2  668.99   374.3     646   384.3  642.92
   484.8  635.07   494.8  633.03   517.4  623.58   524.9  621.56   532.4  624.07
     545  631.54   555.1  632.22   565.1  636.68   635.4  640.07   655.5  649.25
   665.5  651.87   755.9  713.81     776  723.42   856.3  781.46   866.4  784.17
#Mann= 3 , 0 , 0
       0     .08       0   517.4    .045       0   532.4     .08       0
Bank Sta=517.4,532.4
XS Rating Curve= 0 ,0
Exp/Cntr=0.3,0.1

Chan Stop Cuts=-1
Use User Specified Reach Order=0